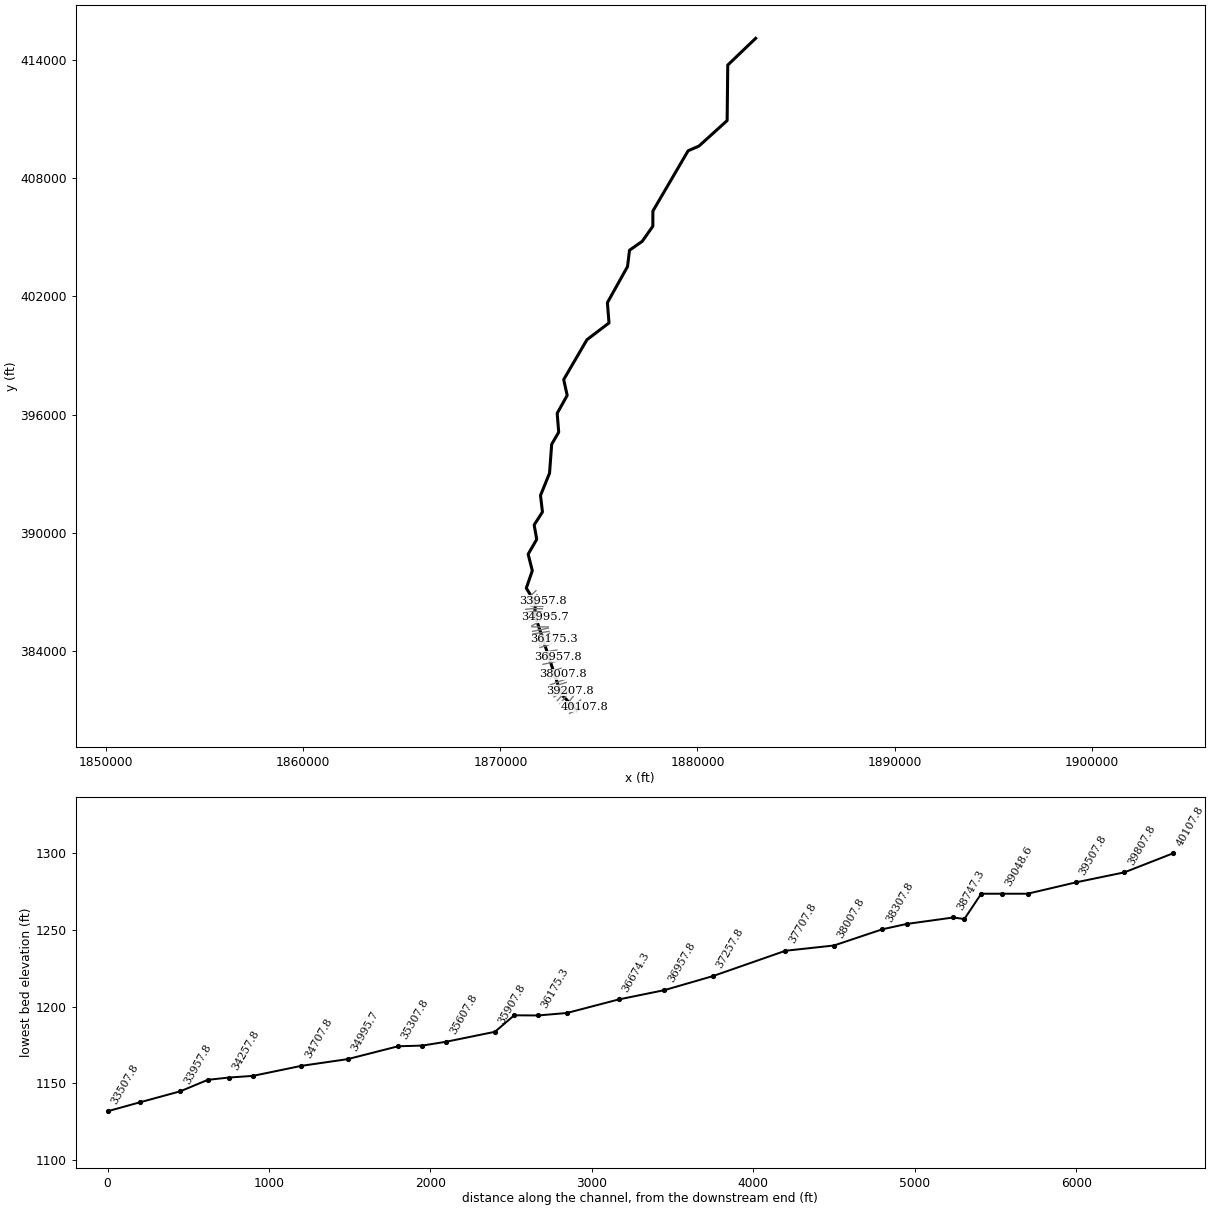
--- ArmstrngCk.prj (project) ---

Proj Title=ArmstrngCk
Current Plan=p01
Default Exp/Contr=0,0
English Units
Geom File=g01
Flow File=f01
Plan File=p01
BEGIN DESCRIPTION:
END DESCRIPTION:
DSS Export Rating Curves= 0
DSS Export Rating Curve Sorted= 0
DSS Export Volume Flow Curves= 0
DXF OffsetX= 0
DXF OffsetY= 0
DXF ScaleX= 0
DXF ScaleY= 0

--- ArmstrngCk.p01 (plan) ---

Plan Title=Floodplain
Program Version=4.00
Geom File=g01
Flow File=f01
K Sum by GR=0
Std Step Tol=0.01
Critical Tol=0.01
Num of Std Step Trials=20
Max Error Tol=0.3
Flow Tol Ratio=0.001
Split Flow NTrial=30
Split Flow Tol=0.02
Split Flow Ratio=0.02
Log Output Level=0
Friction Slope Method=1
Unsteady Friction Slope Method=2
Unsteady Bridges Friction Slope Method=1
Global Log Level=0
CheckData=False
Run HTab=0
Run UNet=0
Run PostProcess=0
UNET Theta=0
UNET Theta Warmup=0
UNET ZTol=0
UNET ZSATol=0
UNET MxIter=0
UNET MaxInSteps=0
UNET DtIC=0
UNET DtMin=0
UNET MaxCRTS=0
UNET WFStab=0
UNET SFStab=0
UNET WFX=0
UNET SFX=0
UNET DSS MLevel=0
UNET DZMax Abort=0
UNET Convert EG Bridges=0
UNET Use Existing IB Tables=0
UNET Froude Limit=0
UNET Froude Power=0
Write IC File=0
Echo Input=False
Echo Output=False
Write Detailed=0

--- ArmstrngCk.f01 (steady flow) ---

Flow Title=NFF Regression Equation
Program Version=4.10
Number of Profiles= 1
Profile Names=P100yr
River Rch & RM=ArmstrngCk,Main            ,40107.8
930.1523
River Rch & RM=ArmstrngCk,Main            ,39807.8
1374.567
River Rch & RM=ArmstrngCk,Main            ,38007.8
1491.052
River Rch & RM=ArmstrngCk,Main            ,36175.3
1625.726
River Rch & RM=ArmstrngCk,Main            ,32907.8
1746.572
River Rch & RM=ArmstrngCk,Main            ,29155.2
1936.086
River Rch & RM=ArmstrngCk,Main            ,25103.9
2150.341
River Rch & RM=ArmstrngCk,Main            ,18318.4
  2382.7
River Rch & RM=ArmstrngCk,Main            ,17607.8
3446.414
River Rch & RM=ArmstrngCk,Main            ,14746.2
3803.024
River Rch & RM=ArmstrngCk,Main            ,5940.3
4193.755
River Rch & RM=ArmstrngCk,Main            ,57.8
4521.351
Boundary for River Rch & Prof#=ArmstrngCk,Main            , 1
Up Type= 0
Dn Type= 3
Dn Slope=0.007624
DSS Import GetInterval= 0
DSS Import GetPeak= 0
DSS Import FillOption= 0

--- ArmstrngCk.g01 (geometry) ---

Geom Title=USGS 3m DEM
Program Version=4.10

River Reach=ArmstrngCk      ,Main
Reach XY= 30
     1873880.094      381018.362     1873084.387      381825.173
     1871740.637      385872.049     1871781.663      386451.411
      1871315.29      387203.646     1871620.846      388089.062
      1871409.04      388924.132     1871844.804      389677.604
     1871714.595      390408.507     1872134.734      391064.834
     1872036.327      391902.295     1872494.109      393031.771
     1872603.484      394498.785     1872959.387       395108.16
     1872882.412      396068.058     1873389.943      396974.479
     1873212.561      397776.835     1874391.679      399797.396
      1875511.47       400648.09     1875429.873      401675.868
     1876450.707      403503.993     1876551.401      404332.118
     1877198.817      404787.617     1877735.429      405550.868
     1877737.165      406318.229      1879526.18      409377.162
     1880072.815      409612.303     1881504.526      410906.771
     1881536.059      413721.111     1882950.965      415075.671

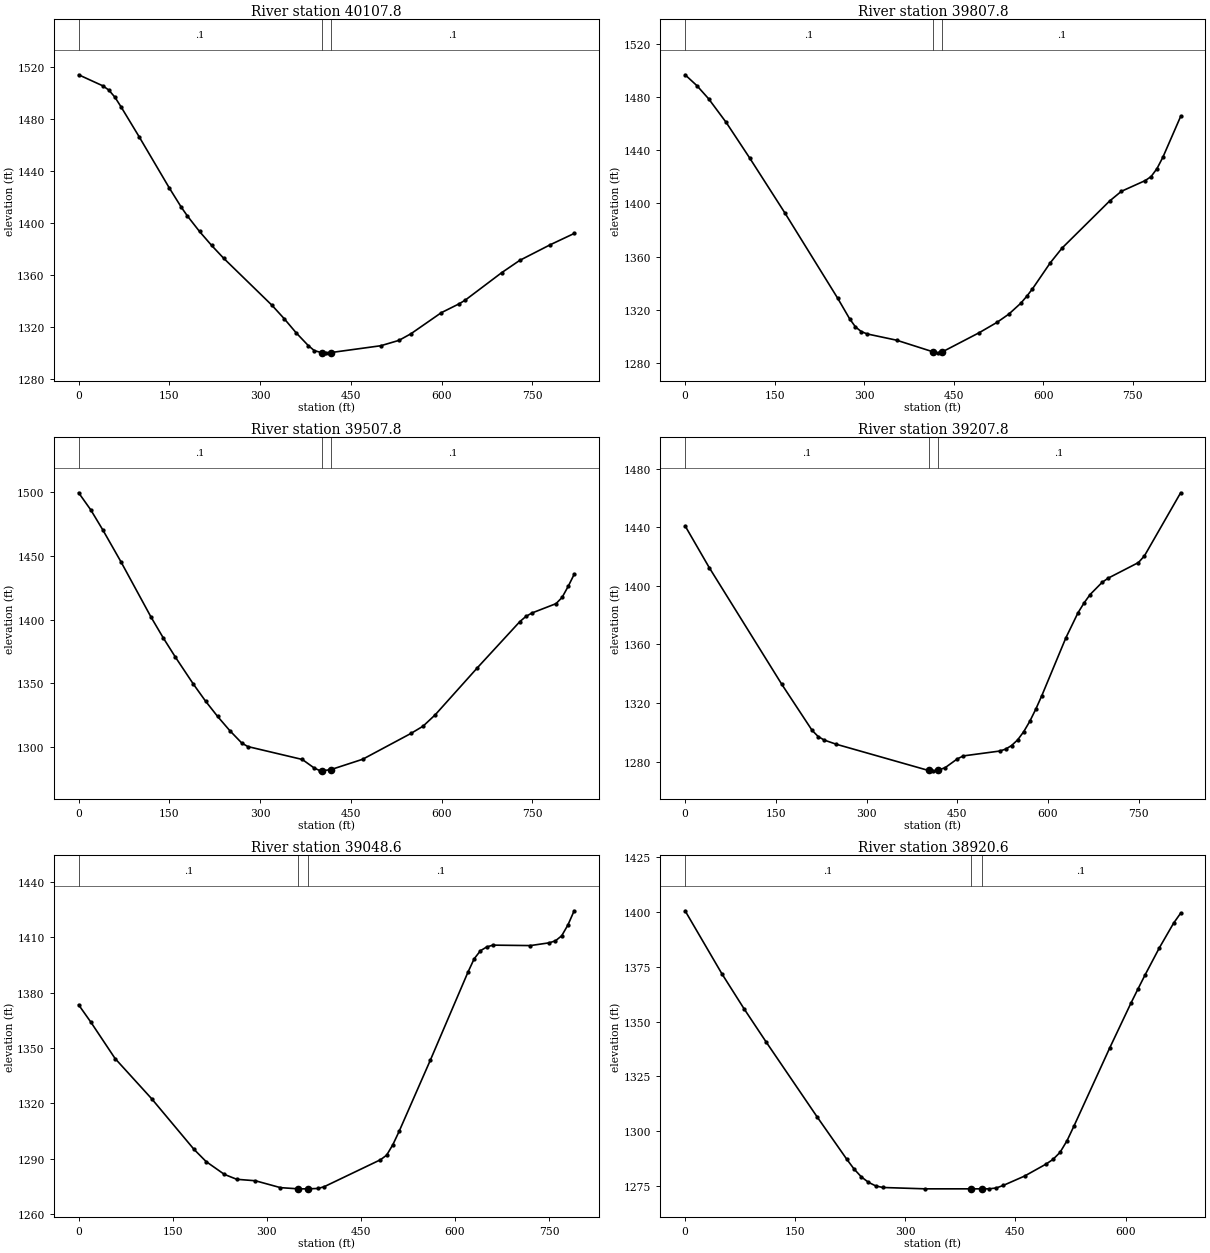
Type RM Length L Ch R = 1 ,40107.8 ,293.6,299.9,304.4
XS GIS Cut Line= 3
     1873504.318      380855.319     1873875.891      381027.436
     1874247.463      381199.552
#Sta/Elev= 30
       0 1514.05      40 1505.54    49.9 1502.28    59.9 1496.83    69.9 1489.52
    99.9 1466.43   149.8 1426.96   169.8 1412.01   179.8 1405.34   199.8 1393.42
   219.7 1382.72   239.7  1372.8   319.6 1336.58   339.6 1326.36   359.6 1315.36
   379.5 1305.61   389.5 1301.71     402 1300.08   409.5 1299.99     417 1300.21
   499.4 1305.46   529.4 1309.59   549.3 1314.71   599.3 1330.87   629.2 1337.81
   639.2 1340.65   699.2 1361.71   729.1 1371.19     779  1383.1     819 1391.89
#Mann= 3 , 0 , 0
       0      .1       0     402    .045       0     417      .1       0
Bank Sta=402,417
XS Rating Curve= 0 ,0
Exp/Cntr=0.3,0.1

Type RM Length L Ch R = 1 ,39807.8 ,295.3,299.9,306.4
XS GIS Cut Line= 3
     1873426.217      381018.613     1873745.176      381296.666
     1874073.859      381536.859
#Sta/Elev= 30
       0 1496.67    19.7 1488.53    39.4 1478.63    68.9 1460.81   108.2  1434.1
   167.3 1392.71   255.8 1328.55   275.5 1313.32   285.4 1307.12   295.2 1303.61
   305.1 1301.82   354.3 1297.13   415.6 1288.35   423.1 1287.62   430.6 1288.26
   492.6 1302.73   522.4 1310.49   542.3 1316.71   562.2 1324.83   572.1 1329.98
     582 1335.75   611.8 1355.31   631.6 1366.41   711.1 1401.72   730.9 1409.05
   770.7 1417.09   780.6 1420.09   790.5 1426.08   800.4 1434.64   830.2 1465.35
#Mann= 3 , 0 , 0
       0      .1       0   415.6    .045       0   430.6      .1       0
Bank Sta=415.6,430.6
XS Rating Curve= 0 ,0
Exp/Cntr=0.3,0.1

Type RM Length L Ch R = 1 ,39507.8 ,299.9,300,300.2
XS GIS Cut Line= 3
     1873252.779      381144.889      1873501.93      381469.872
     1873751.082      381794.855
#Sta/Elev= 30
       0 1499.75      20 1486.35      40 1470.52    69.9 1445.52   119.8 1401.87
   139.8 1385.69   159.8 1370.61   189.8 1349.18   209.7 1335.95   229.7 1323.86
   249.7 1312.78   269.7 1302.92   279.7 1300.17   369.6 1290.04   389.5 1283.26
   399.5 1281.09     402 1281.11     417 1282.07   469.4 1290.19   549.3 1310.52
   569.3 1316.23   589.3 1325.13   659.2 1362.24   729.1 1398.38   739.1 1402.46
   749.1  1405.2     789 1412.56     799 1417.45     809 1426.07     819 1435.62
#Mann= 3 , 0 , 0
       0      .1       0     402    .045       0     417      .1       0
Bank Sta=402,417
XS Rating Curve= 0 ,0
Exp/Cntr=0.3,0.1

Type RM Length L Ch R = 1 ,39207.8 ,164.4,159,153.5
XS GIS Cut Line= 3
      1873028.88       381341.68     1873277.527      381667.732
     1873523.169      381995.255
#Sta/Elev= 30
       0 1440.97      40  1412.4     160 1332.67     210 1301.31     220 1297.11
     230 1294.68     250 1291.82   402.5 1273.91     410 1273.66   417.5 1273.99
     430 1275.82     450 1281.79     460 1283.85   519.9 1287.16   529.9 1288.46
   539.8 1290.94   549.8 1294.76   559.8 1300.32   569.8 1307.36   579.8 1315.71
   589.8 1324.96   629.7 1364.57   649.7 1381.62   659.7 1388.31   669.7 1394.06
   689.6  1402.4   699.6 1405.26   749.6  1415.9   759.5 1420.45   819.4 1463.56
#Mann= 3 , 0 , 0
       0      .1       0   402.5    .045       0   417.5      .1       0
Bank Sta=402.5,417.5
XS Rating Curve= 0 ,0
Exp/Cntr=0.3,0.1

Type RM Length L Ch R = 1 ,39048.6 ,137.6,128,118.4
XS GIS Cut Line= 3
      1872887.69      381505.047     1873055.251      381679.663
     1873475.116       382031.65
#Sta/Elev= 30
       0 1373.45    19.4  1364.1    58.1 1344.33   116.2 1322.61   183.9 1295.07
   203.3 1288.42   232.3  1281.5     252 1278.84   281.8 1278.04   321.7 1274.31
   350.2 1273.66   365.2 1273.66   381.5 1273.86   391.4 1274.81   481.1 1289.43
     491 1291.92     501 1297.69     511 1304.94   560.8 1343.58   620.6 1391.16
   630.5 1398.42   640.5 1402.78   650.4 1404.82   660.4 1405.82   720.2 1405.58
     750 1407.07     760 1408.14     770 1410.89   779.9 1416.73   789.9 1424.45
#Mann= 3 , 0 , 0
       0      .1       0   350.2    .045       0   365.2      .1       0
Bank Sta=350.2,365.2
XS Rating Curve= 0 ,0
Exp/Cntr=0.3,0.1

Type RM Length L Ch R = 1 ,38920.6 ,102.4,104.7,107
XS GIS Cut Line= 4
     1872719.455      381689.252     1872923.123      381816.545
     1873184.652      381885.977     1873323.516      381973.925
#Sta/Elev= 30
       0 1400.66      50 1371.96    80.1 1356.02   110.1 1340.89   180.1 1306.41
   220.2  1287.2   230.2 1282.71   240.2 1279.09   249.8 1276.65   259.5 1275.03
   269.2 1274.28   327.2 1273.66   389.3 1273.66   404.3 1273.66   414.1 1273.67
   423.8 1274.05   433.4 1275.21   462.4 1279.48   491.4  1284.9   501.1 1287.08
   510.8 1290.31   520.4  1295.7   530.1 1302.58   578.4 1337.96   607.4 1358.49
   617.1 1365.03   626.8 1371.46   646.1 1383.74   665.5    1395   675.1 1399.56
#Mann= 3 , 0 , 0
       0      .1       0   389.3    .045       0   404.3      .1       0
Bank Sta=389.3,404.3
XS Rating Curve= 0 ,0
Exp/Cntr=0.3,0.1

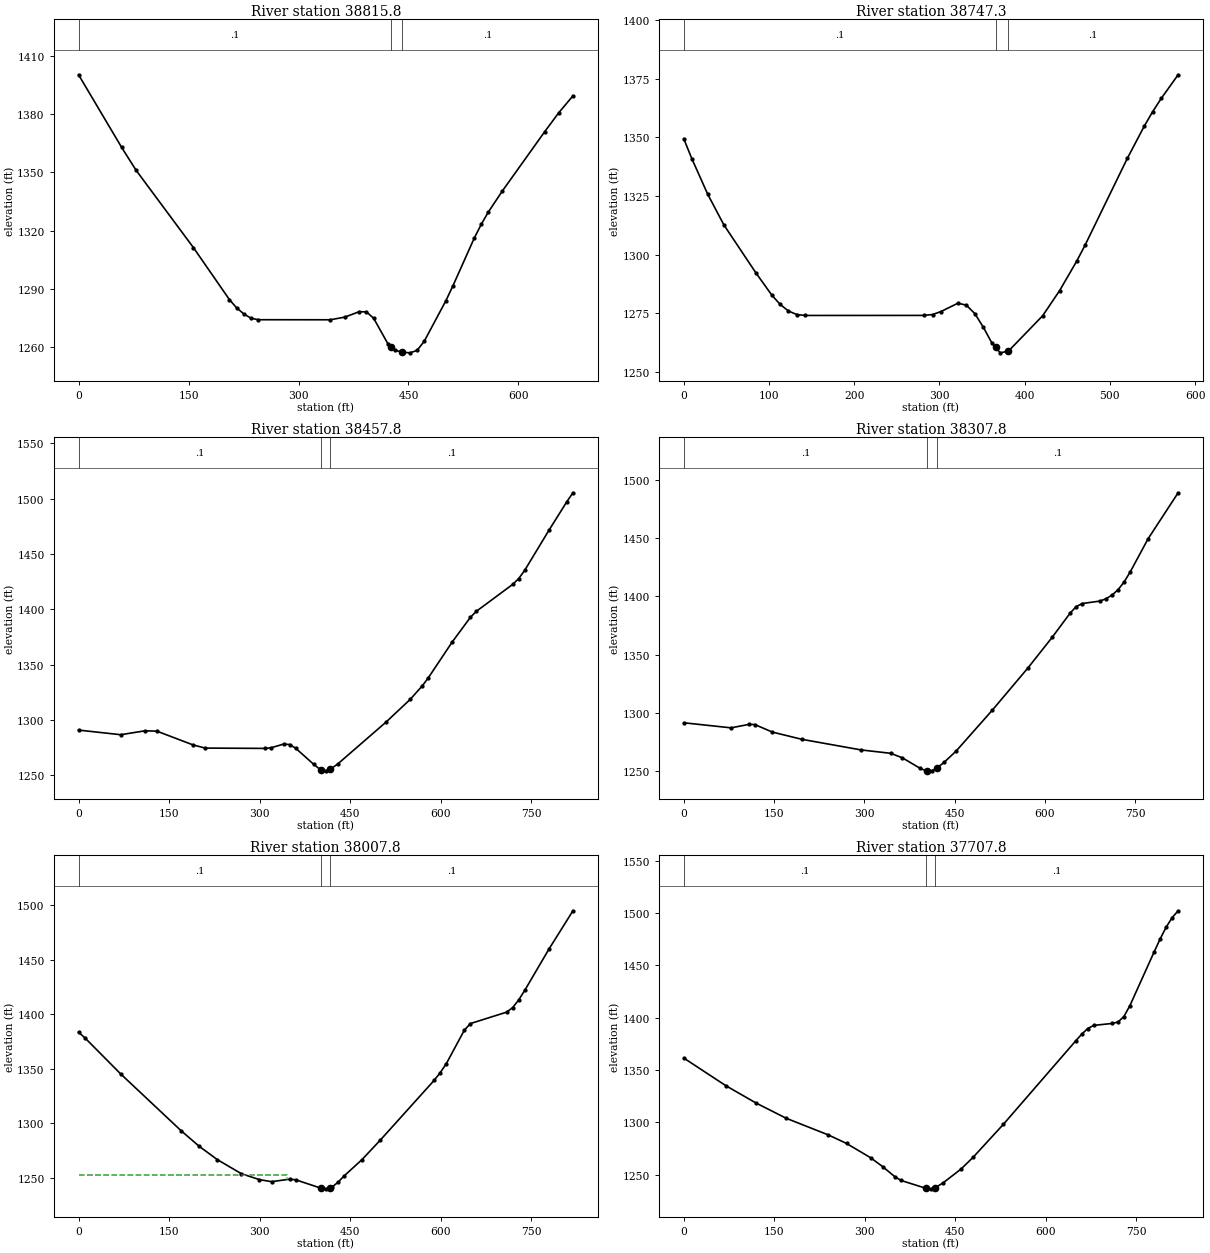
Type RM Length L Ch R = 1 ,38815.8 ,70.4,68.6,66.7
XS GIS Cut Line= 4
      1872664.26      381776.569      1872870.91      381888.673
     1873119.429      381983.219     1873280.157       382048.05
#Sta/Elev= 30
       0  1400.1    58.8 1362.73    78.4 1351.02   156.7  1311.2   205.7 1284.52
   215.5 1280.26   225.3 1277.16   235.1 1274.94     245 1274.15   343.4 1274.12
   363.1 1275.49   382.8 1278.28   392.7 1278.18   402.5 1274.87   422.2 1261.58
   426.1 1260.34   432.1 1258.42   441.1 1257.48   451.8 1257.12   461.6 1258.34
   471.4 1263.03     501 1283.92   510.6 1291.58   539.5 1315.95   549.1 1323.12
   558.8 1329.47     578 1340.34   635.8 1370.85     655 1380.61   674.3 1389.26
#Mann= 3 , 0 , 0
       0      .1       0   426.1    .045       0   441.1      .1       0
Bank Sta=426.1,441.1
XS Rating Curve= 0 ,0
Exp/Cntr=0.3,0.1

Type RM Length L Ch R = 1 ,38747.3 ,289,289.5,290
XS GIS Cut Line= 3
      1872686.16      381898.967     1872786.108      381951.642
     1873234.524      382082.655
#Sta/Elev= 30
       0 1349.38     9.4 1340.95    28.2 1325.66    47.1 1312.65    84.7 1292.19
   103.6 1282.61     113 1278.83   122.9 1275.95   132.9 1274.43   142.8 1274.07
     282 1274.09   291.9 1274.46   301.8 1275.74   321.7 1279.29   331.6 1278.46
   341.6 1274.83   351.5 1269.06   361.5 1262.37     366 1260.45   371.4 1258.14
     381 1258.89   421.1 1273.93     441 1284.64   460.9  1297.1   470.8 1303.95
   520.5 1341.03   540.4 1354.78   550.3 1360.96   560.3 1366.58   580.1 1376.64
#Mann= 3 , 0 , 0
       0      .1       0     366    .045       0     381      .1       0
Bank Sta=366,381
XS Rating Curve= 0 ,0
Exp/Cntr=0.3,0.1

Type RM Length L Ch R = 1 ,38457.8 ,148.6,150,150.9
XS GIS Cut Line= 3
     1872563.606      382178.968     1872954.098      382302.282
      1873344.59      382425.595
#Sta/Elev= 30
       0 1290.75    69.9 1286.56   109.9  1290.1   129.8 1289.77   189.8 1277.32
   209.7 1274.48   309.6 1274.18   319.6 1274.88   339.6 1278.07   349.6 1277.71
   359.6 1274.37   389.5  1259.8   399.5 1255.45     402 1255.06   409.5  1253.9
     417 1255.31   429.5 1260.18   509.4 1298.01   549.3 1318.47   569.3 1330.67
   579.3 1337.96   619.2 1370.59   649.2 1392.79   659.2 1398.27   719.1 1422.49
   729.1 1427.74   739.1 1435.25     779 1471.25     809  1497.4     819 1505.36
#Mann= 3 , 0 , 0
       0      .1       0     402    .045       0     417      .1       0
Bank Sta=402,417
XS Rating Curve= 0 ,0
Exp/Cntr=0.3,0.1

Type RM Length L Ch R = 1 ,38307.8 ,301.4,300,299.5
XS GIS Cut Line= 3
     1872524.882      382297.613     1872909.965      382445.515
     1873294.854      382583.776
#Sta/Elev= 30
       0 1291.65    78.6  1287.3     108 1290.23   117.9 1290.16   147.3 1283.65
   196.4 1277.44   294.6 1268.37   343.8 1265.47   363.4 1261.55   392.9 1252.56
   402.7 1250.43     405 1250.46   412.5 1250.57     420  1252.6   432.5 1257.67
   452.4 1267.28   512.3 1302.19   572.1 1338.78     612 1364.81   641.9 1385.58
   651.9 1391.18   661.9 1393.89   691.8 1396.03   701.8 1398.05   711.8  1401.2
   721.7 1405.75   731.7  1412.4   741.7 1420.83   771.6 1449.45   821.5 1488.88
#Mann= 3 , 0 , 0
       0      .1       0     405    .045       0     420      .1       0
Bank Sta=405,420
XS Rating Curve= 0 ,0
Exp/Cntr=0.3,0.1

Type RM Length L Ch R = 1 ,38007.8 ,298.8,300,300.8
XS GIS Cut Line= 3
      1872398.89      382593.615     1872789.671      382716.265
     1873178.144      382845.756
#Sta/Elev= 30
       0 1383.62      10 1378.72    69.9 1345.26   169.8 1293.24   199.8 1278.92
   229.8 1266.69   269.7 1253.75   299.7 1248.29   319.7 1246.43   349.6 1248.68
   359.6 1248.17   402.1 1240.36   409.6 1239.84   417.1 1240.96   419.6 1241.34
   429.6 1245.74   439.5 1251.45   469.5 1266.63   499.5 1284.31   589.4  1339.6
   599.3 1346.57   609.3 1354.78   639.3 1385.64   649.3 1391.58   709.2 1402.05
   719.2 1406.23   729.2 1413.25   739.2 1422.02   779.1 1459.72   819.1 1495.11
#Mann= 3 , 0 , 0
       0      .1       0   402.1    .045       0   417.1      .1       0
#XS Ineff= 2 , 0
          344.55 1252.68
Permanent Ineff=
       F       F
Bank Sta=402.1,417.1
XS Rating Curve= 0 ,0
Exp/Cntr=0.3,0.1

Type RM Length L Ch R = 1 ,37707.8 ,453.3,450,446.9
XS GIS Cut Line= 3
      1872306.69      382855.462     1872690.117      382999.247
     1873073.543      383143.032
#Sta/Elev= 30
       0 1361.37    69.9  1334.9   119.8 1318.38   169.8 1303.82   239.7 1287.87
   269.7 1279.77   309.6  1266.1   329.6  1257.6   349.6 1248.04   359.6 1244.49
     402 1236.77   409.5 1236.41     417 1237.63   429.5 1242.06   459.4 1255.35
   479.4 1266.59   529.4 1297.99   649.2  1377.7   659.2 1384.12   669.2 1389.54
   679.2 1392.57   709.1 1394.39   719.1 1395.71   729.1 1400.91   739.1 1411.46
     779 1462.44     789 1474.92     799 1486.28     809 1495.43     819 1502.07
#Mann= 3 , 0 , 0
       0      .1       0     402    .045       0     417      .1       0
Bank Sta=402,417
XS Rating Curve= 0 ,0
Exp/Cntr=0.3,0.1

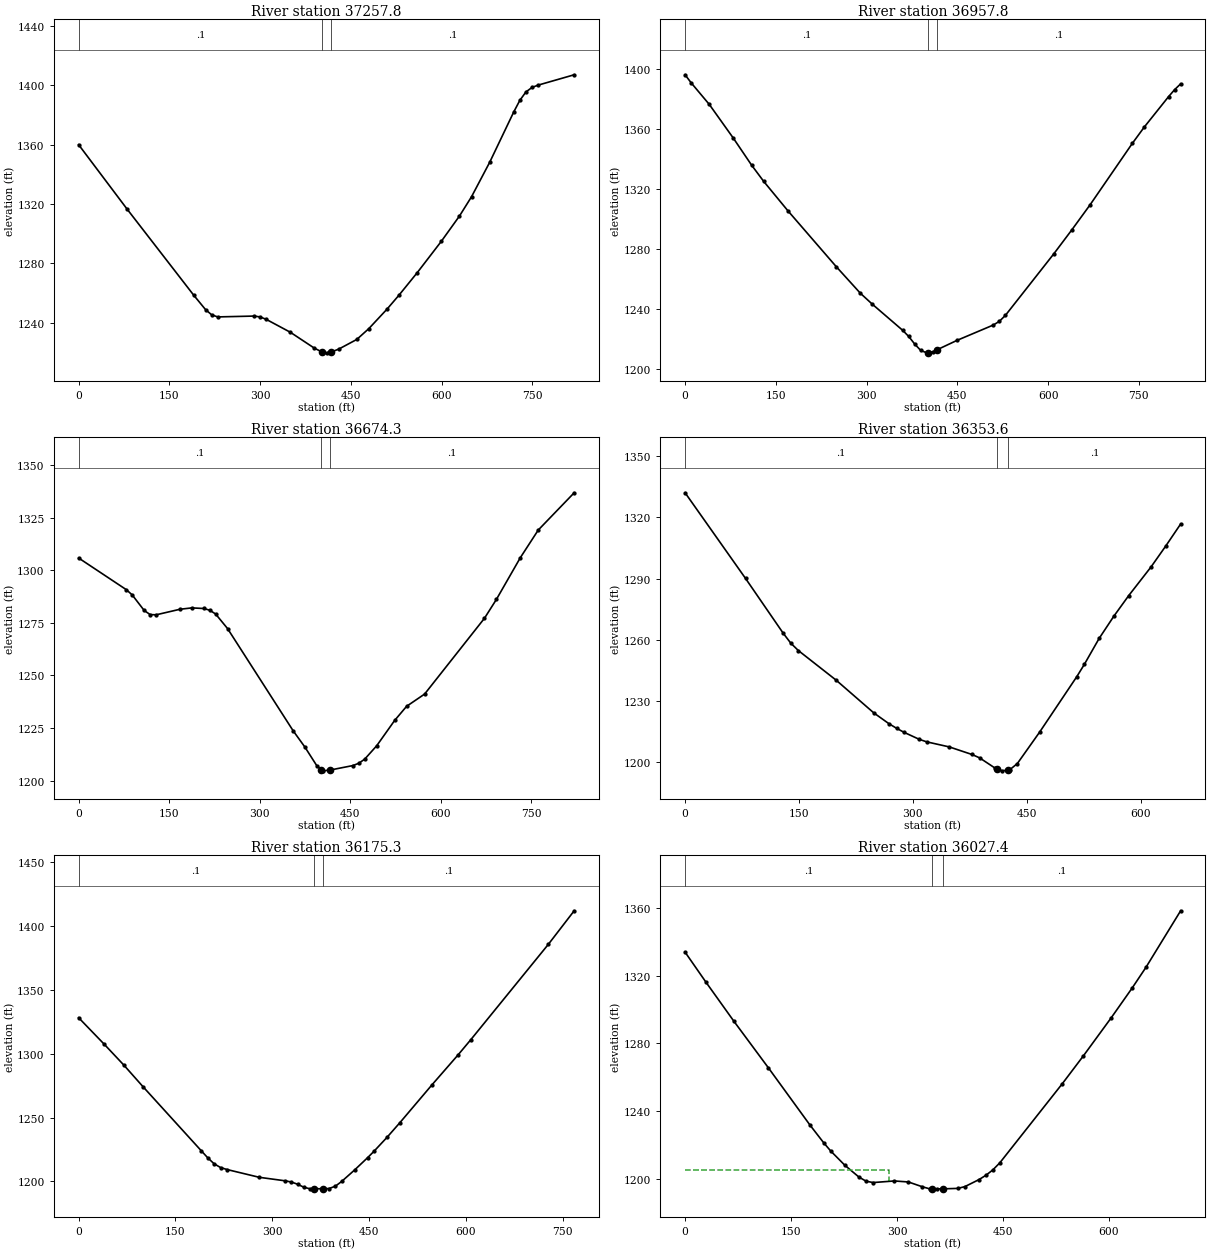
Type RM Length L Ch R = 1 ,37257.8 ,304.7,300,294.9
XS GIS Cut Line= 3
     1872159.508      383342.531     1872560.256      383428.357
     1872959.423      383518.903
#Sta/Elev= 30
       0 1359.94      80 1316.64   189.9 1258.81   209.9 1248.88   219.9 1245.44
   229.9 1244.02   289.9 1244.59   299.9 1244.02   309.9 1242.42   349.9  1233.7
   389.8 1222.95   402.3 1220.43   409.8 1219.84   417.3 1220.38   429.8 1222.32
   459.8 1228.86   479.7 1236.15   509.7 1249.23   529.6 1258.69   559.6 1273.76
   599.5  1294.9   629.5 1311.93   649.4 1324.88   679.4 1348.05   719.3 1382.04
   729.3 1389.79   739.3 1395.42   749.3 1398.45   759.2    1400   819.1    1407
#Mann= 3 , 0 , 0
       0      .1       0   402.3    .045       0   417.3      .1       0
Bank Sta=402.3,417.3
XS Rating Curve= 0 ,0
Exp/Cntr=0.3,0.1

Type RM Length L Ch R = 1 ,36957.8 ,279.2,283.4,287.3
XS GIS Cut Line= 3
     1872095.026      383721.579     1872504.526      383721.579
     1872914.026      383721.579
#Sta/Elev= 30
       0 1396.02      10 1390.67      40 1376.25    79.9 1353.68   109.9  1335.8
   129.8 1325.02   169.8 1305.42   249.7 1268.18   289.6 1250.44   309.6 1243.05
   359.6  1225.7   369.6  1221.6   379.5 1216.54   389.5 1212.27   399.5 1210.69
     402 1210.87   409.5 1211.41     417 1212.84   449.4    1219   509.4 1229.23
   519.4 1231.69   529.4 1235.67   609.3 1276.64   639.2 1292.67   669.2 1309.28
   739.1 1350.26   759.1 1361.28     799 1381.42     809 1386.08     819 1389.96
#Mann= 3 , 0 , 0
       0      .1       0     402    .045       0     417      .1       0
Bank Sta=402,417
XS Rating Curve= 0 ,0
Exp/Cntr=0.3,0.1

Type RM Length L Ch R = 1 ,36674.3 ,318.3,320.6,323.2
XS GIS Cut Line= 3
     1872056.791      383922.925     1872454.262      383998.689
     1872864.473      384070.219
#Sta/Elev= 30
       0  1305.9      79 1290.83    88.8 1288.32   108.6 1280.94   118.4 1278.98
   128.3 1278.86   167.8  1281.5   187.5 1282.16   207.2 1281.87   217.1 1281.07
     227 1279.24   246.7 1272.33   355.3 1223.71     375 1215.86   394.8 1206.94
     402 1205.22   404.6  1204.6     417    1205   454.2  1207.1   464.1 1208.19
     474 1210.18   493.9 1216.56   523.6  1228.6   543.4 1235.32   573.2 1241.14
   672.3 1277.19   692.1 1286.17   731.8 1306.06   761.5 1319.22     821 1336.95
#Mann= 3 , 0 , 0
       0      .1       0     402    .045       0     417      .1       0
Bank Sta=402,417
XS Rating Curve= 0 ,0
Exp/Cntr=0.3,0.1

Type RM Length L Ch R = 1 ,36353.6 ,175.5,178.3,181
XS GIS Cut Line= 3
     1872008.369      384192.736     1872446.741      384323.591
     1872607.247       384434.71
#Sta/Elev= 30
       0 1332.02    79.6 1290.05   129.3 1263.15   139.2 1258.34   149.2  1254.7
   198.9 1240.21   248.6 1224.14   268.5 1218.86   278.5 1216.62   288.4 1214.63
   308.3 1211.22   318.2 1209.97   348.1 1207.47   377.9 1203.77   387.9 1202.12
   407.8 1197.22   410.9 1196.76   417.7 1195.76   425.9  1196.2   427.6 1196.29
   437.6 1199.32   467.2 1214.86     516 1241.96   525.8 1247.89   545.3 1260.62
   564.8 1271.58   584.4 1281.68   613.7 1295.68   633.2 1305.99   652.7 1316.71
#Mann= 3 , 0 , 0
       0      .1       0   410.9    .045       0   425.9      .1       0
Bank Sta=410.9,425.9
XS Rating Curve= 0 ,0
Exp/Cntr=0.3,0.1

Type RM Length L Ch R = 1 ,36175.3 ,142.6,147.9,154
XS GIS Cut Line= 4
     1871981.099      384339.466     1872280.945      384450.585
     1872361.343        384485.6     1872700.728      384605.799
#Sta/Elev= 30
       0 1328.19      40 1307.23      70 1291.09    99.9 1274.05   189.9    1224
   199.9 1218.49   209.8 1213.79   219.8 1210.84   229.8 1209.28   279.8 1203.18
   319.8 1200.44   329.5 1199.49   339.3 1197.73     349 1195.34   358.8 1194.15
   364.2 1194.21   379.2 1194.25     388 1194.39   397.7 1196.25   407.5 1199.98
   427.5 1208.96   447.5 1218.52   457.5 1223.59   477.5 1234.41   497.5 1245.93
   547.5 1275.75   587.5 1298.96   607.5 1311.04   727.5 1385.67   767.5 1411.95
#Mann= 3 , 0 , 0
       0      .1       0   364.2    .045       0   379.2      .1       0
Bank Sta=364.2,379.2
XS Rating Curve= 0 ,0
Exp/Cntr=0.3,0.1

Type RM Length L Ch R = 1 ,36027.4 ,121.9,119.6,118.6
XS GIS Cut Line= 4
     1871949.827      384396.346     1872128.821      384498.628
     1872292.079      384630.415     1872553.686      384744.499
#Sta/Elev= 30
       0 1333.87    29.4 1316.24    68.7 1293.33   117.8  1265.7   176.7 1231.91
   196.3 1221.36   206.2 1216.54   226.1 1208.18   246.1 1201.19   256.1 1198.79
   266.1 1197.96   296.1 1198.91   316.1 1198.31     336 1195.45     346 1194.29
   349.9 1194.28     356 1194.26   364.9 1194.26     386 1194.52     396 1195.57
     416 1199.72   425.8 1202.26   435.6 1205.44   445.5 1209.62   534.1 1256.38
   563.6 1272.62     603 1295.08   632.5 1312.55   652.2 1324.85   701.4 1358.28
#Mann= 3 , 0 , 0
       0      .1       0   349.9    .045       0   364.9      .1       0
#XS Ineff= 2 , 0
          289.11 1205.34
Permanent Ineff=
       F       F
Bank Sta=349.9,364.9
XS Rating Curve= 0 ,0
Exp/Cntr=0.3,0.1

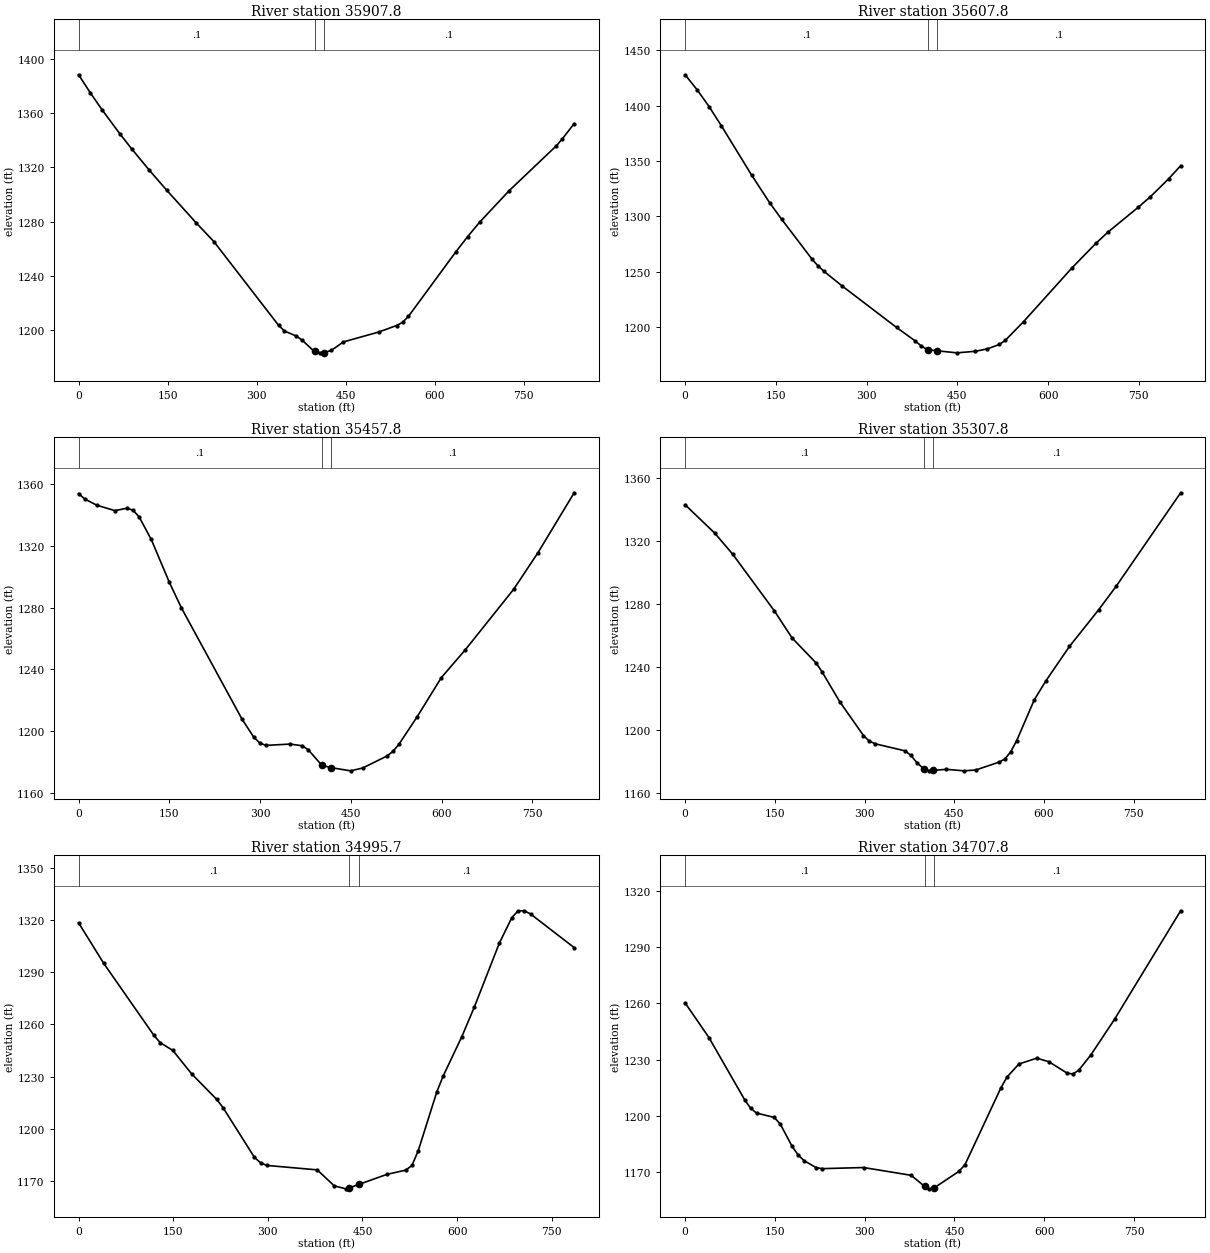
Type RM Length L Ch R = 1 ,35907.8 ,308.7,300,289.3
XS GIS Cut Line= 3
     1871806.633      384452.587     1872153.751      384663.338
     1872499.118      384917.549
#Sta/Elev= 30
       0 1388.25    19.8 1374.88    39.6 1362.41    69.3 1344.87    89.1 1333.87
   118.8 1318.12   148.6 1303.13   198.1 1279.18   227.8 1265.44   336.8  1203.8
   346.7 1199.56   366.5 1195.89   376.4 1192.88   396.2 1184.86   398.6 1184.53
   406.1 1183.48   413.6 1183.61     426 1185.34     446 1191.51   505.8 1198.83
   535.7 1203.61   545.7 1205.93   555.7 1210.35   635.5 1257.84   655.4 1269.05
   675.4 1279.58   725.2 1302.84     805 1335.99     815  1341.1   834.9 1352.27
#Mann= 3 , 0 , 0
       0      .1       0   398.6    .045       0   413.6      .1       0
Bank Sta=398.6,413.6
XS Rating Curve= 0 ,0
Exp/Cntr=0.3,0.1

Type RM Length L Ch R = 1 ,35607.8 ,149,150,151.1
XS GIS Cut Line= 3
     1871658.739      384881.719     1872063.014      384946.924
     1872467.289      385012.128
#Sta/Elev= 30
       0 1427.83      20 1414.22      40 1398.84    59.9 1381.87   109.9 1337.37
   139.8 1312.36   159.8 1297.33   209.7 1261.58   219.7 1255.46   229.7 1250.49
   259.7 1237.26   349.6 1199.88   379.5 1188.07   389.5 1183.58   399.5 1180.13
     402 1179.84     417 1178.83   449.4 1177.02   479.4  1178.4   499.4 1180.55
   519.4 1184.57   529.4 1188.39   559.3  1205.1   639.2 1253.51   679.2 1275.94
   699.2 1286.07   749.1  1308.4   769.1 1317.87     799 1333.88     819 1345.81
#Mann= 3 , 0 , 0
       0      .1       0     402    .045       0     417      .1       0
Bank Sta=402,417
XS Rating Curve= 0 ,0
Exp/Cntr=0.3,0.1

Type RM Length L Ch R = 1 ,35457.8 ,154.4,149.9,145.1
XS GIS Cut Line= 3
     1871637.581      385012.151     1872038.638      385094.917
     1872439.224      385179.888
#Sta/Elev= 30
       0 1353.67      10 1350.14      30 1346.13    59.9 1342.61    79.9 1344.18
    89.9 1342.86    99.9 1338.62   119.9  1324.1   149.8  1296.4   169.8 1279.82
   269.7  1208.1   289.6 1196.14   299.6 1192.43   309.6 1190.92   349.6 1191.77
   369.6 1190.69   379.5 1188.09     402 1178.05     417 1176.56   449.5 1174.48
   469.4  1176.3   509.4    1184   519.4 1187.03   529.4 1191.66   559.3 1209.29
   599.3 1234.64   639.2 1252.77   719.1 1291.85   759.1  1315.4     819 1354.15
#Mann= 3 , 0 , 0
       0      .1       0     402    .045       0     417      .1       0
Bank Sta=402,417
XS Rating Curve= 0 ,0
Exp/Cntr=0.3,0.1

Type RM Length L Ch R = 1 ,35307.8 ,295.2,312.2,329.5
XS GIS Cut Line= 3
     1871600.495      385238.623     1872007.998      385241.098
     1872428.816      385238.883
#Sta/Elev= 30
       0 1343.12    49.7 1325.04    79.5 1311.72   149.1 1275.74   178.9 1258.43
   218.7 1242.69   228.6 1237.15   258.4    1218   298.2 1196.45   308.1 1192.85
   318.1 1191.18   367.8  1186.7   377.7 1183.77   387.6 1179.08     400 1175.02
   407.5 1174.15     415 1174.33   436.9 1174.98   466.2 1174.02   485.8 1174.55
     525 1179.57   534.7 1181.62   544.5  1186.3   554.3 1193.25   583.7 1219.17
   603.2 1231.28   642.4 1253.06   691.3 1276.39   720.7  1291.4   828.3 1350.73
#Mann= 3 , 0 , 0
       0      .1       0     400    .045       0     415      .1       0
Bank Sta=400,415
XS Rating Curve= 0 ,0
Exp/Cntr=0.3,0.1

Type RM Length L Ch R = 1 ,34995.7 ,292.8,287.5,280.4
XS GIS Cut Line= 4
     1871592.973      385290.866      1871921.32      385478.493
     1871987.336      385541.035      1872240.98      385730.399
#Sta/Elev= 30
       0 1318.32    39.8 1295.08   119.4 1253.72   129.4 1249.53   149.3 1245.11
   179.1 1231.66   218.9 1216.98   228.9 1212.27   278.6 1183.76   288.6  1180.5
   298.6 1179.07   378.2 1176.52   405.4 1167.32   423.6 1165.63   428.9 1166.18
   443.9 1168.14   488.9 1173.95   518.6 1176.38   528.5 1179.08   538.4 1187.52
     568 1221.46   577.9 1230.38   607.6 1253.09   627.4 1270.08     667 1306.71
   686.7  1321.3   696.6 1325.23   706.5 1325.27   716.4 1323.44   785.6 1304.12
#Mann= 3 , 0 , 0
       0      .1       0   428.9    .045       0   443.9      .1       0
Bank Sta=428.9,443.9
XS Rating Curve= 0 ,0
Exp/Cntr=0.3,0.1

Type RM Length L Ch R = 1 ,34707.8 ,308.5,300,293.3
XS GIS Cut Line= 3
     1871436.488      385538.233     1871789.538      385741.916
     1872169.625      385921.352
#Sta/Elev= 30
       0 1260.27    39.8 1241.81    99.4 1208.73   109.4 1204.17   119.3  1201.6
   149.1 1199.24   159.1 1195.66   178.9 1183.79   188.9 1179.27   198.8 1176.22
   218.7 1172.58   228.6 1171.98   298.2 1172.58   377.8 1168.43   400.1 1162.53
   407.6 1161.23   415.1 1161.54   457.6 1170.56   467.6 1174.09   527.7 1215.06
   537.7 1220.73   557.7 1227.73   587.7 1230.83   607.7 1228.93   637.8 1222.93
   647.8 1222.37   657.8 1224.44   677.8 1232.51   717.8  1251.7   827.9 1309.32
#Mann= 3 , 0 , 0
       0      .1       0   400.1    .045       0   415.1      .1       0
Bank Sta=400.1,415.1
XS Rating Curve= 0 ,0
Exp/Cntr=0.3,0.1

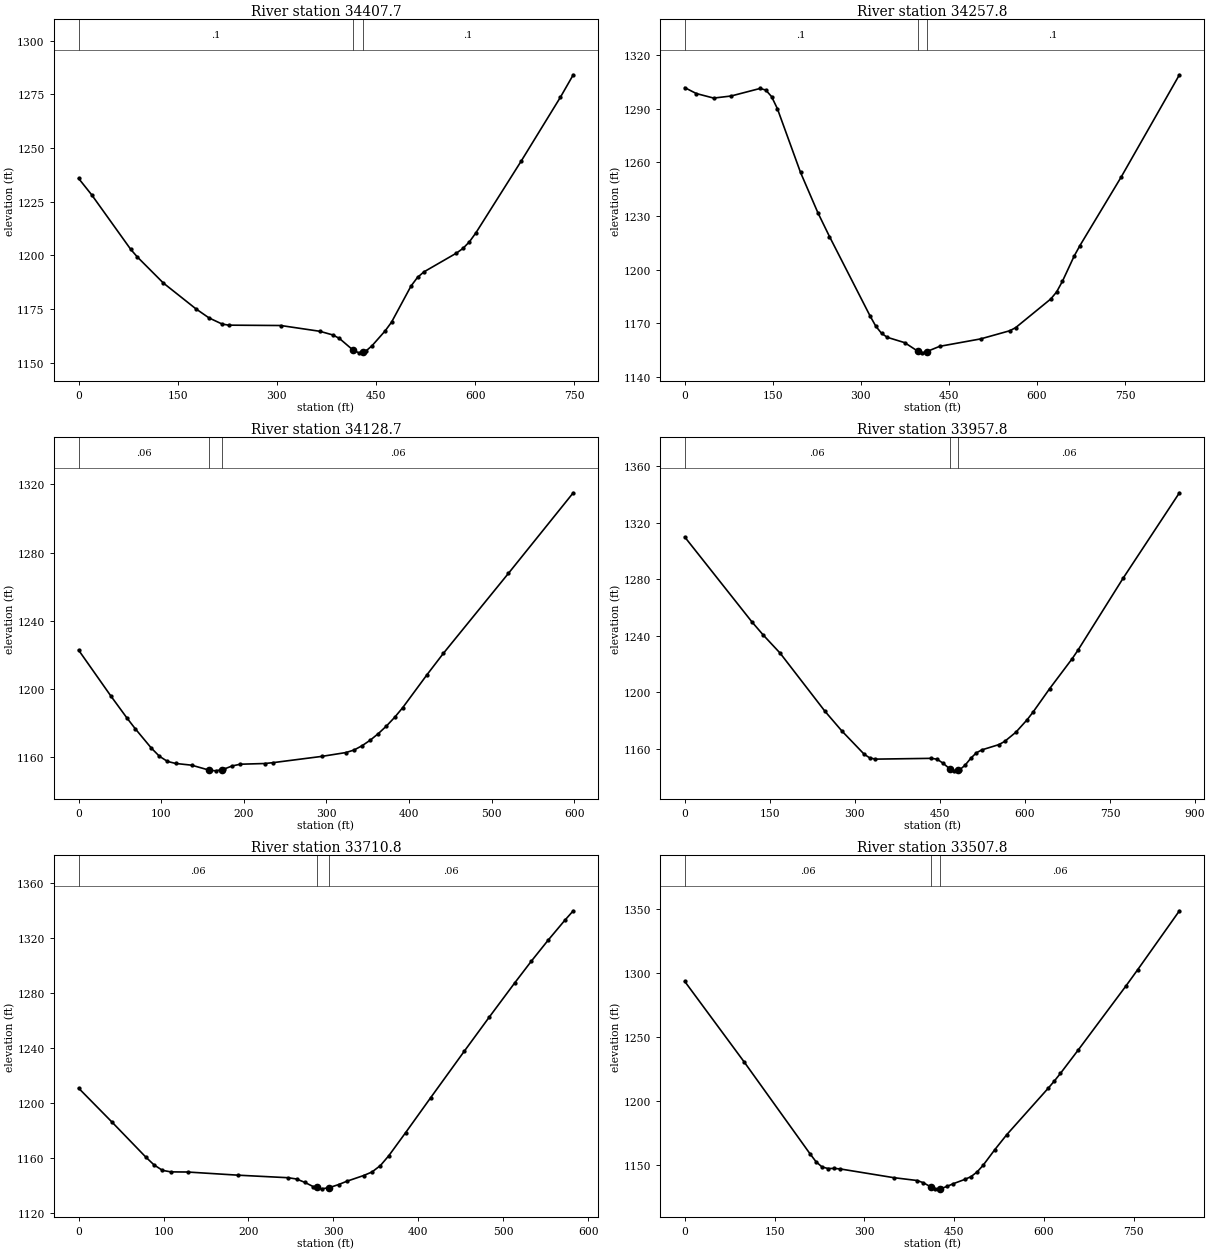
Type RM Length L Ch R = 1 ,34407.7 ,150.8,149.6,145.6
XS GIS Cut Line= 3
     1871324.195      385967.081     1871772.972      386034.472
     1872065.762      386002.724
#Sta/Elev= 30
       0 1235.88    19.7 1228.29    78.9 1202.84    88.8 1199.34   128.2 1187.19
   177.6 1175.14   197.3 1170.94     217  1168.1   226.9 1167.57   305.8  1167.4
     365 1164.71   384.8 1162.99   394.6 1161.37   415.4  1155.9   424.2 1154.68
   430.4 1155.12   434.1 1155.38   443.9 1157.99   463.6 1164.85   473.4 1168.96
   502.9 1185.79   512.7 1189.81   522.5 1192.39   571.6 1201.11   581.4 1203.28
   591.2 1206.36   601.1 1210.58   669.8 1244.08   728.7  1273.6   748.3 1284.13
#Mann= 3 , 0 , 0
       0      .1       0   415.4    .045       0   430.4      .1       0
Bank Sta=415.4,430.4
XS Rating Curve= 0 ,0
Exp/Cntr=0.3,0.1

Type RM Length L Ch R = 1 ,34257.8 ,131.9,129.1,128.9
XS GIS Cut Line= 3
      1871293.53      386131.809     1871695.876      386171.437
     1872133.963      386157.956
#Sta/Elev= 30
       0 1301.75    19.7 1298.45    49.3 1295.91    78.9 1297.07   128.2 1301.28
     138 1300.41   147.9 1296.73   157.8 1289.99   197.2 1254.38   226.8 1231.85
   246.5 1218.58   315.6 1174.24   325.4 1168.49   335.3 1164.46   345.1 1162.25
   374.7 1159.27   396.8 1154.54   404.3 1153.59   411.8 1154.23   434.2 1157.22
   503.9 1161.37   553.7 1165.94   563.7 1167.68   623.4 1183.67   633.4  1187.6
   643.4 1193.62   663.3 1207.64   673.2 1213.55     743 1251.59   842.6 1308.93
#Mann= 3 , 0 , 0
       0      .1       0   396.8    .045       0   411.8      .1       0
Bank Sta=396.8,411.8
XS Rating Curve= 0 ,0
Exp/Cntr=0.3,0.1

Type RM Length L Ch R = 1 ,34128.7 ,166.2,170.8,178.4
XS GIS Cut Line= 3
     1871559.419      386302.244     1871735.331      386296.133
     1872157.479      386274.349
#Sta/Elev= 30
       0 1222.85    39.1 1195.93    58.7 1182.96    68.4 1176.89      88 1165.47
    97.8 1160.66   107.6 1157.63   117.4 1156.44   136.9 1155.42   158.3 1152.48
   166.2 1152.11   173.3 1152.86     176 1153.14   185.8 1154.96   195.7 1155.99
   225.2  1156.4     235 1156.89     294 1160.55   323.5 1162.82   333.3 1164.29
   343.1 1166.82     353 1170.08   362.8 1173.93   372.6 1178.38   382.5 1183.44
   392.3 1189.14   421.8  1208.5   441.4 1220.88   520.1 1267.73   598.7 1315.02
#Mann= 3 , 0 , 0
       0     .06       0   158.3    .045       0   173.3     .06       0
Bank Sta=158.3,173.3
XS Rating Curve= 0 ,0
Exp/Cntr=0.3,0.1

Type RM Length L Ch R = 1 ,33957.8 ,232.4,246.9,258.7
XS GIS Cut Line= 3
     1871314.164      386369.067     1871781.543      386451.751
     1872162.176      386567.215
#Sta/Elev= 30
       0 1309.91   118.7 1249.79   138.4 1240.63   168.1 1227.86   247.2 1186.76
   276.9 1172.88   316.4 1156.37   326.3 1153.74   336.2 1152.89   435.1 1153.44
     445 1152.83   454.9 1150.18   467.1 1146.13   474.6 1144.61   482.1 1145.08
   484.6 1145.24   494.5 1148.64   504.5 1153.52   514.4 1157.39   524.4 1159.48
   554.2 1163.17   564.1 1165.37     584 1171.91   603.9 1180.77   613.8 1185.88
   643.7 1202.79   683.5 1224.01   693.4 1229.85     773 1280.72   872.4 1341.17
#Mann= 3 , 0 , 0
       0     .06       0   467.1    .045       0   482.1     .06       0
Bank Sta=467.1,482.1
XS Rating Curve= 0 ,0
Exp/Cntr=0.3,0.1

Type RM Length L Ch R = 1 ,33710.8 ,201.8,203.1,201.6
XS GIS Cut Line= 2
     1871458.404      386447.617     1871855.775      386873.245
#Sta/Elev= 30
       0 1210.68    39.5  1185.9      79 1160.66    88.8 1154.92    98.7 1150.95
   108.6 1149.84   128.3 1149.74   187.5 1147.45   246.7 1145.59   256.6 1144.66
   266.5 1142.16   276.3 1139.11   280.1  1138.5   286.2 1137.52   295.1  1138.4
     306  1140.6   315.8 1143.04   335.6  1147.2   345.4 1149.77   355.3 1154.45
   365.2 1161.62   384.9 1178.29   414.5 1203.78     454 1237.48   483.6 1262.42
   513.2 1286.96   532.9 1302.87   552.7 1318.14   572.4 1332.63   582.3 1339.51
#Mann= 3 , 0 , 0
       0     .06       0   280.1    .045       0   295.1     .06       0
Bank Sta=280.1,295.1
XS Rating Curve= 0 ,0
Exp/Cntr=0.3,0.1

Type RM Length L Ch R = 1 ,33507.8 ,269.8,255.9,244.8
XS GIS Cut Line= 3
     1871239.666      386477.262     1871509.538      386797.299
      1871807.13      387076.025
#Sta/Elev= 30
       0 1293.37    99.7 1230.28   209.3 1158.92   219.3 1152.76   229.2  1148.7
   239.2 1147.46   249.2 1147.51   259.2 1147.16   348.9 1140.33   388.7 1138.07
   398.7 1136.31   411.1 1133.12   418.6  1131.6   426.1  1131.8   428.6 1131.87
   438.5 1133.56   448.5 1135.59   468.4 1139.05   478.3 1141.14   488.2 1144.69
   498.2 1149.82   518.1 1162.23     538 1173.87   607.6 1210.28   617.5 1215.72
   627.5 1221.56   657.3 1239.86   736.9 1289.72   756.8 1302.58   826.4 1348.46
#Mann= 3 , 0 , 0
       0     .06       0   411.1    .045       0   426.1     .06       0
Bank Sta=411.1,426.1
XS Rating Curve= 0 ,0
Exp/Cntr=0.3,0.1