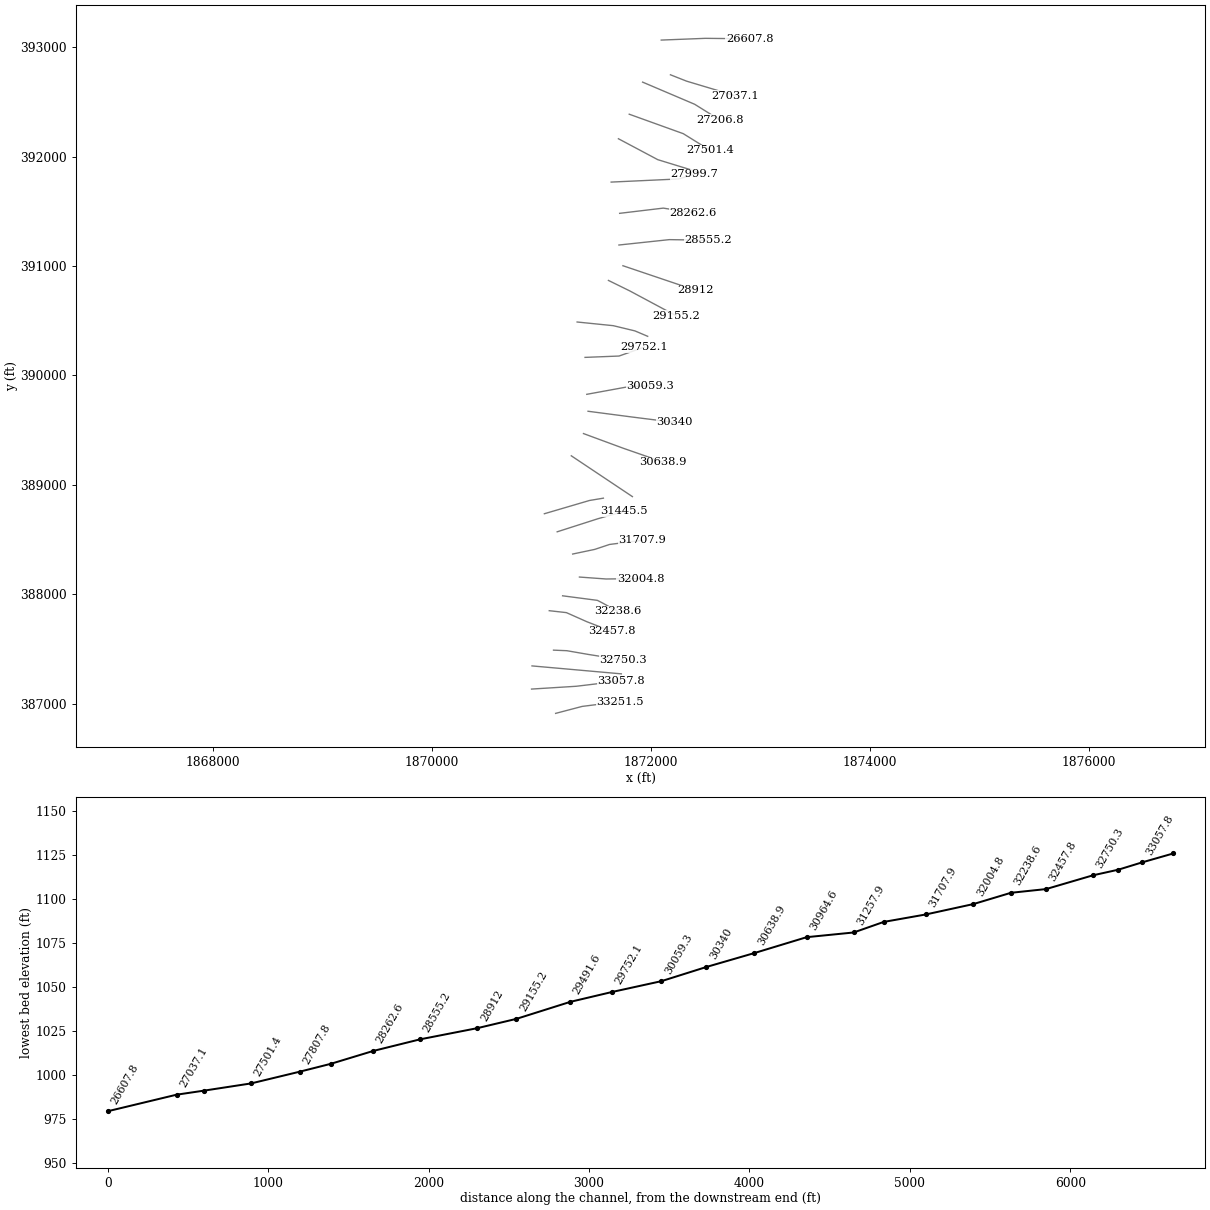
HEC-RAS study ArmstrngCk.prj: ArmstrngCk

--- ArmstrngCk.g01 (geometry) --- (continued)

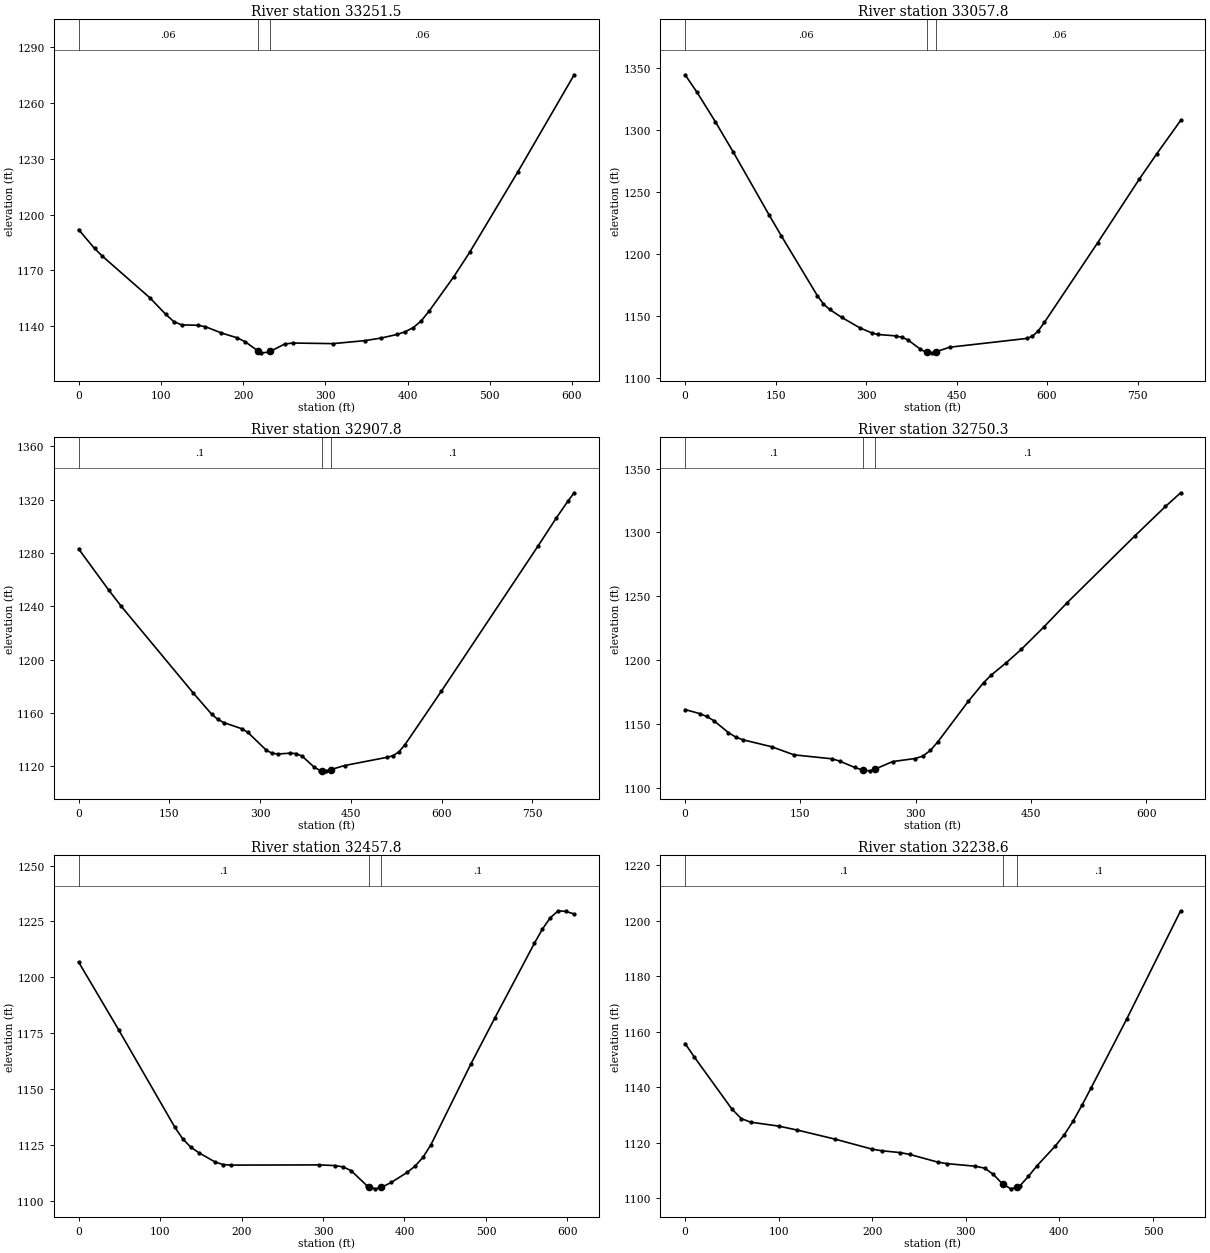
Type RM Length L Ch R = 1 ,33251.5 ,198.4,194,190.8
XS GIS Cut Line= 3
      1871129.91      386913.866     1871372.304      386977.539
     1871721.552      387021.597
#Sta/Elev= 30
       0 1191.94    19.3 1181.85    28.9 1177.64    86.8  1155.2     106 1146.35
   115.7 1142.48   125.3  1140.7   144.6 1140.51   154.2 1139.72   173.5 1136.38
   192.8 1133.74   202.4 1131.68   218.2 1126.68   221.7 1125.67   231.3 1126.01
   233.2 1126.49   250.6 1130.41   260.4 1130.95   309.3 1130.62   348.4 1132.25
     368 1133.64   387.5 1135.59   397.3 1137.05   407.1 1139.28   416.8 1142.94
   426.6 1148.34     456 1166.48   475.5 1179.71   534.2 1223.06   602.6 1275.19
#Mann= 3 , 0 , 0
       0     .06       0   218.2    .045       0   233.2     .06       0
Bank Sta=218.2,233.2
XS Rating Curve= 0 ,0
Exp/Cntr=0.3,0.1

Type RM Length L Ch R = 1 ,33057.8 ,153.4,150,145.3
XS GIS Cut Line= 3
      1870909.76      387135.897      1871317.93      387161.408
     1871727.542      387210.361
#Sta/Elev= 30
       0 1344.39      20 1330.13    49.9 1306.79    79.8 1282.24   139.6 1231.29
   159.6 1214.69   219.4 1166.51   229.4 1159.94   239.4 1155.62   259.3 1149.24
   289.3 1140.82   309.2 1136.72   319.2 1135.41   349.1 1134.26   359.1 1133.15
   369.1 1131.14     389 1123.95     399 1121.13   401.5    1121     409 1120.62
   416.5 1121.54   438.4 1125.13   566.1 1132.19   575.9 1133.95   585.8  1138.5
   595.6  1145.1     684 1209.25   752.7 1260.23   782.2 1280.99   821.5 1307.63
#Mann= 3 , 0 , 0
       0     .06       0   401.5    .045       0   416.5     .06       0
Bank Sta=401.5,416.5
XS Rating Curve= 0 ,0
Exp/Cntr=0.3,0.1

Type RM Length L Ch R = 1 ,32907.8 ,159.3,157.5,155.6
XS GIS Cut Line= 3
     1870914.094      387347.353     1871321.986      387311.098
     1871729.878      387274.842
#Sta/Elev= 30
       0 1283.08    49.9 1252.05    69.9 1240.28   189.8 1174.69   219.7 1159.02
   229.7 1155.19   239.7 1152.68   269.7 1148.04   279.7 1145.29   309.6 1132.18
   319.6 1129.63   329.6 1129.08   349.6 1129.69   359.6 1129.39   369.6 1127.38
   389.5 1119.14   399.5 1116.61     402 1116.56   409.5 1116.43     417 1117.39
   439.5 1120.41   509.4 1126.56   519.4 1127.76   529.4 1130.69   539.3 1136.03
   599.3  1176.1   759.1 1285.12     789 1305.97     809 1319.17     819  1325.2
#Mann= 3 , 0 , 0
       0      .1       0     402    .045       0     417      .1       0
Bank Sta=402,417
XS Rating Curve= 0 ,0
Exp/Cntr=0.3,0.1

Type RM Length L Ch R = 1 ,32750.3 ,298.1,292.6,288.1
XS GIS Cut Line= 4
     1871110.483      387491.378     1871232.387      387486.261
     1871426.614      387452.524     1871748.043      387401.307
#Sta/Elev= 30
       0 1161.27    18.8 1158.13    28.2 1155.84    37.5 1152.49    56.3 1143.22
    65.7 1139.75    75.1  1137.6   112.6 1132.12   141.7 1125.77     191 1122.68
   200.9 1120.91   220.6 1115.92   231.6 1113.72   240.3 1113.25   246.6 1114.43
   269.9 1120.51   299.4 1122.91   309.3 1124.83   319.2 1129.33     329 1136.14
   368.5 1167.82   388.2 1182.25     398 1188.18   417.8 1197.94   437.5 1208.52
   467.1 1226.22   496.7 1244.82   585.4 1297.52   624.9 1320.38   644.6 1331.09
#Mann= 3 , 0 , 0
       0      .1       0   231.6    .045       0   246.6      .1       0
Bank Sta=231.6,246.6
XS Rating Curve= 0 ,0
Exp/Cntr=0.3,0.1

Type RM Length L Ch R = 1 ,32457.8 ,220.3,219,216.7
XS GIS Cut Line= 4
     1871071.629      387851.661     1871228.071        387834.1
     1871416.973      387750.142     1871644.693      387662.086
#Sta/Elev= 30
       0 1206.82    49.2  1176.5   118.1 1132.98   127.9 1127.73   137.8 1124.04
   147.6 1121.58   167.3 1117.48   177.1 1116.31     187 1116.05   295.2 1116.14
   314.9 1115.84   324.8 1115.23   334.6 1113.54   354.3 1106.72   356.6 1106.42
   364.1 1105.44   371.6 1106.09   383.7 1108.29   403.2 1112.76     413 1115.61
   422.7 1119.52   432.5 1125.18   481.3 1161.13   510.6 1181.62   559.5 1215.25
   569.2  1221.5     579 1226.67   588.8 1229.76   598.5 1229.46   608.3 1228.31
#Mann= 3 , 0 , 0
       0      .1       0   356.6    .045       0   371.6      .1       0
Bank Sta=356.6,371.6
XS Rating Curve= 0 ,0
Exp/Cntr=0.3,0.1

Type RM Length L Ch R = 1 ,32238.6 ,222.9,233.8,244.8
XS GIS Cut Line= 4
      1871193.49       387987.65     1871510.927      387946.134
     1871560.837      387920.539      1871695.06      387846.363
#Sta/Elev= 30
       0  1155.7      10 1150.78      50  1132.1      60 1128.66      70 1127.37
     100 1125.94     120 1124.51   160.1 1121.26   200.1 1117.62   210.1 1117.06
   230.1 1116.39   240.1 1115.73   270.1 1112.96   280.1  1112.4   310.1 1111.49
   320.1 1110.79   329.5 1108.51   339.3 1105.08   348.2 1103.33   354.3 1103.96
   357.5 1104.29   366.9 1107.82   376.2 1111.68   395.4 1118.68     405  1122.7
   414.6  1127.7   424.2  1133.5   433.7 1139.58   472.1 1164.63   529.6 1203.56
#Mann= 3 , 0 , 0
       0      .1       0   339.3    .045       0   354.3      .1       0
Bank Sta=339.3,354.3
XS Rating Curve= 0 ,0
Exp/Cntr=0.3,0.1

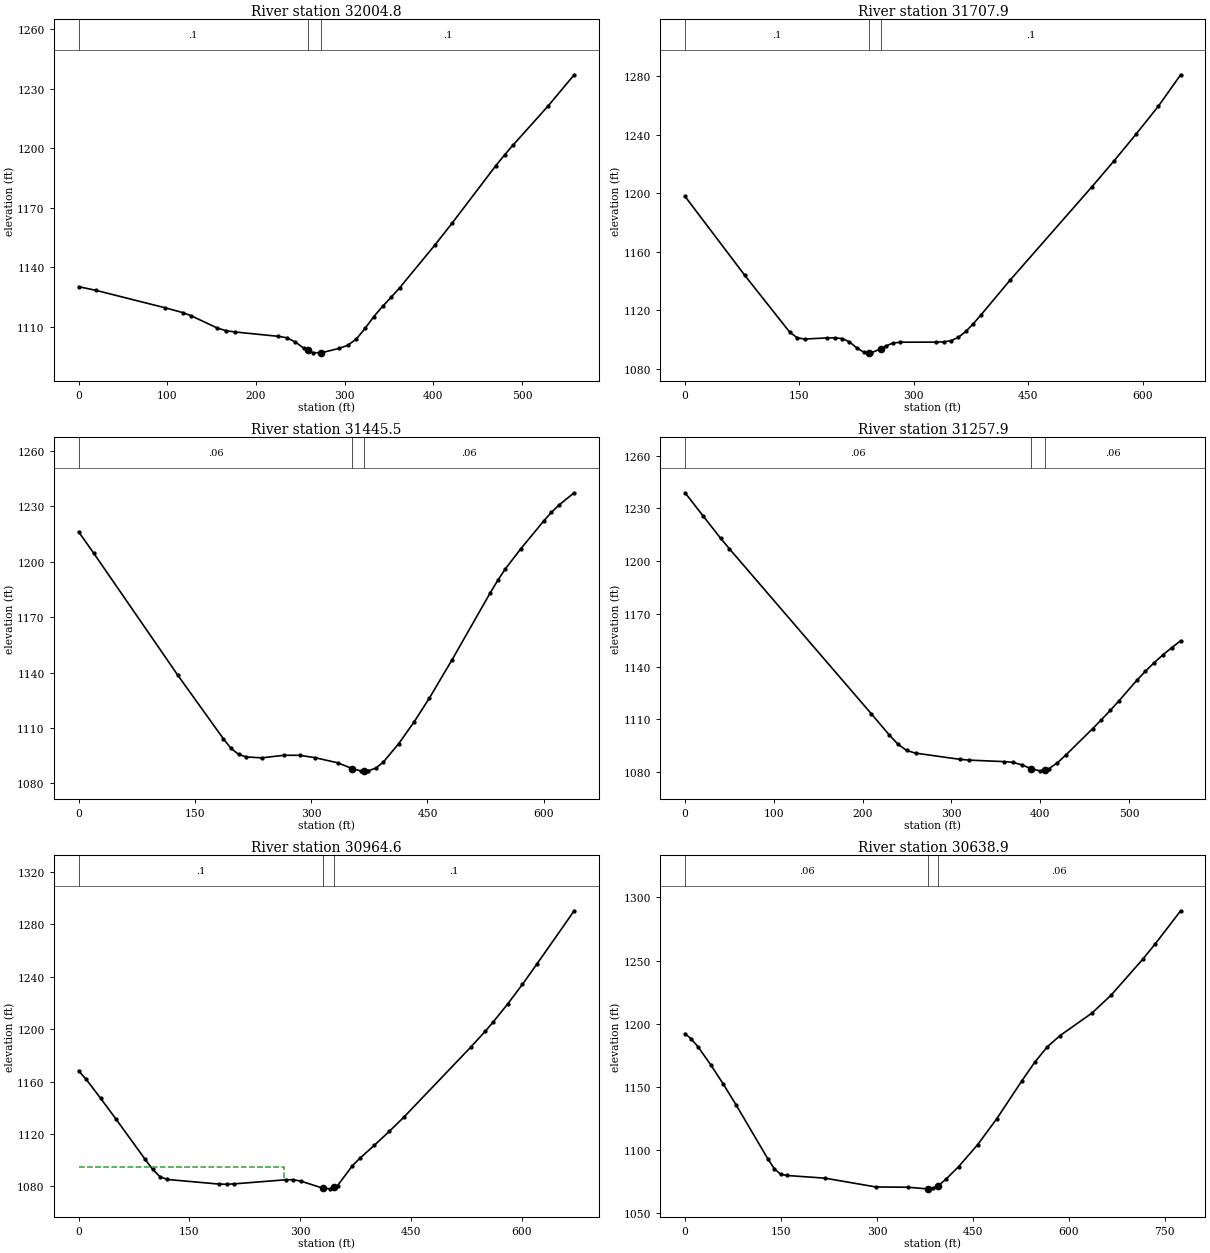
Type RM Length L Ch R = 1 ,32004.8 ,289.8,296.9,303.9
XS GIS Cut Line= 3
      1871347.14      388158.961     1871590.861        388141.3
     1871905.225      388144.833
#Sta/Elev= 30
       0 1130.28    19.6 1128.42    97.7 1119.62   117.3 1117.23   127.1 1115.58
   156.4 1109.42   166.2 1108.11   175.9 1107.47   224.8 1105.28   234.6 1104.55
   244.4  1102.4   254.2 1099.14   258.4 1098.24     264 1097.04   273.4 1096.94
   293.5 1099.17   303.3  1100.7   313.1  1103.9     323 1109.28   332.8 1115.21
   342.6 1120.31   352.4 1124.95   362.2 1129.86   401.6 1151.24   421.2 1162.37
   470.3 1191.23   480.2 1196.66     490 1201.76   529.3 1221.33   558.7 1237.07
#Mann= 3 , 0 , 0
       0      .1       0   258.4    .045       0   273.4      .1       0
Bank Sta=258.4,273.4
XS Rating Curve= 0 ,0
Exp/Cntr=0.3,0.1

Type RM Length L Ch R = 1 ,31707.9 ,262.6,262.4,262.1
XS GIS Cut Line= 4
     1871285.327      388369.126     1871486.661      388411.513
     1871622.297      388456.725      1871921.12      388494.519
#Sta/Elev= 30
       0 1197.75    78.4 1143.84   137.2 1105.16     147 1101.32   156.8 1100.44
   186.2 1101.24     196 1101.29   205.8 1100.78   215.3 1098.62   224.8 1094.56
   234.3 1091.49   241.5 1091.15   243.9 1091.04   256.5 1093.74   262.9 1095.67
   272.5 1097.66     282  1098.3   329.7 1098.35   339.2 1098.52   348.7 1099.35
   358.4 1101.64   368.2 1105.66   377.9 1110.86   387.6 1116.64   426.4 1140.77
   533.3 1204.22   562.5 1222.02   591.6 1240.41   620.8 1259.43   649.9  1280.8
#Mann= 3 , 0 , 0
       0      .1       0   241.5    .045       0   256.5      .1       0
Bank Sta=241.5,256.5
XS Rating Curve= 0 ,0
Exp/Cntr=0.3,0.1

Type RM Length L Ch R = 1 ,31445.5 ,187.9,187.3,186.8
XS GIS Cut Line= 3
     1871144.039      388572.227     1871518.451      388692.322
     1871755.107      388759.433
#Sta/Elev= 30
       0 1216.21    19.7 1204.51   127.8 1138.66   186.8 1104.12   196.6 1098.95
   206.4  1095.7   216.3 1094.34   235.9 1093.84   265.4 1095.25   285.1 1095.22
   304.7 1093.96   334.2 1091.16   353.1 1087.98   363.7 1086.81   368.1 1086.82
   373.5 1086.84   383.4 1088.26   393.2 1091.63   412.9 1101.55   432.6 1113.23
   452.2 1126.04   481.8 1147.03     531 1183.23   540.8 1190.04   550.6 1196.25
   570.3 1207.03   599.8 1222.02   609.7 1226.73   619.5  1230.7   639.2 1237.36
#Mann= 3 , 0 , 0
       0     .06       0   353.1    .045       0   368.1     .06       0
Bank Sta=353.1,368.1
XS Rating Curve= 0 ,0
Exp/Cntr=0.3,0.1

Type RM Length L Ch R = 1 ,31257.9 ,312.7,292.9,273.1
XS GIS Cut Line= 3
     1871027.064      388737.294     1871438.977      388858.334
     1871566.135      388879.527
#Sta/Elev= 30
       0 1238.82      20 1225.82    39.9 1213.05    49.9    1207   209.7 1113.28
   229.6 1101.44   239.6 1096.04   249.6 1092.38   259.6 1090.88   309.5 1087.36
   319.5 1086.92   359.4 1086.06   369.4 1085.65   379.4  1084.2   390.2 1081.95
   399.4 1080.82   405.2 1081.44   409.4 1081.89   419.3 1085.36   429.3 1090.01
   459.1 1104.81     469 1109.89   478.9 1115.15   488.8 1120.63   508.7 1132.19
   518.6 1137.46   528.5 1142.35   538.4 1146.79   548.3 1150.85   558.2 1154.73
#Mann= 3 , 0 , 0
       0     .06       0   390.2    .045       0   405.2     .06       0
Bank Sta=390.2,405.2
XS Rating Curve= 0 ,0
Exp/Cntr=0.3,0.1

Type RM Length L Ch R = 1 ,30964.6 ,320.8,326,331.6
XS GIS Cut Line= 2
     1871272.964      389266.302     1871831.049      388893.656
#Sta/Elev= 30
       0 1168.21      10 1161.87      30  1147.1    50.1 1131.78    90.1 1100.64
   100.2 1093.09   110.2 1087.41   120.2 1085.31   190.3 1081.78   200.3 1081.67
   210.3 1081.94   280.4 1085.07   290.5 1085.12   300.5 1084.11   331.1 1078.61
   340.5 1078.16   346.1 1079.52   350.6 1080.62   370.6 1095.63   380.6 1101.35
   400.6 1111.47   420.7    1122   440.7 1133.01   530.8 1186.15   550.9 1198.53
   560.9 1205.13   580.9  1219.1     601 1234.18     621 1250.01   671.1 1290.34
#Mann= 3 , 0 , 0
       0      .1       0   331.1    .045       0   346.1      .1       0
#XS Ineff= 2 , 0
          278.39 1094.57
Permanent Ineff=
       F       F
Bank Sta=331.1,346.1
XS Rating Curve= 0 ,0
Exp/Cntr=0.3,0.1

Type RM Length L Ch R = 1 ,30638.9 ,293.9,298.9,303.7
XS GIS Cut Line= 3
     1871384.228      389469.403     1871748.043      389335.179
     1872113.624      389208.021
#Sta/Elev= 30
       0 1192.16     9.9 1187.73    19.9 1181.89    39.8 1167.62    59.7 1152.19
    79.6 1135.77   129.3 1092.98   139.2 1085.26   149.2 1080.76   159.1 1079.74
   218.8  1077.6   298.3 1070.64     348 1070.44   377.8 1069.15   380.2 1069.24
   387.8 1069.53   395.2 1071.38   407.6 1076.66   427.5 1086.67   457.3 1104.06
     487 1124.46   526.7 1154.83   546.6 1169.38   566.4  1181.7   586.3 1190.56
   635.9 1208.31   665.7 1222.38   715.3 1250.89   735.2 1263.28   774.8 1289.43
#Mann= 3 , 0 , 0
       0     .06       0   380.2    .045       0   395.2     .06       0
Bank Sta=380.2,395.2
XS Rating Curve= 0 ,0
Exp/Cntr=0.3,0.1

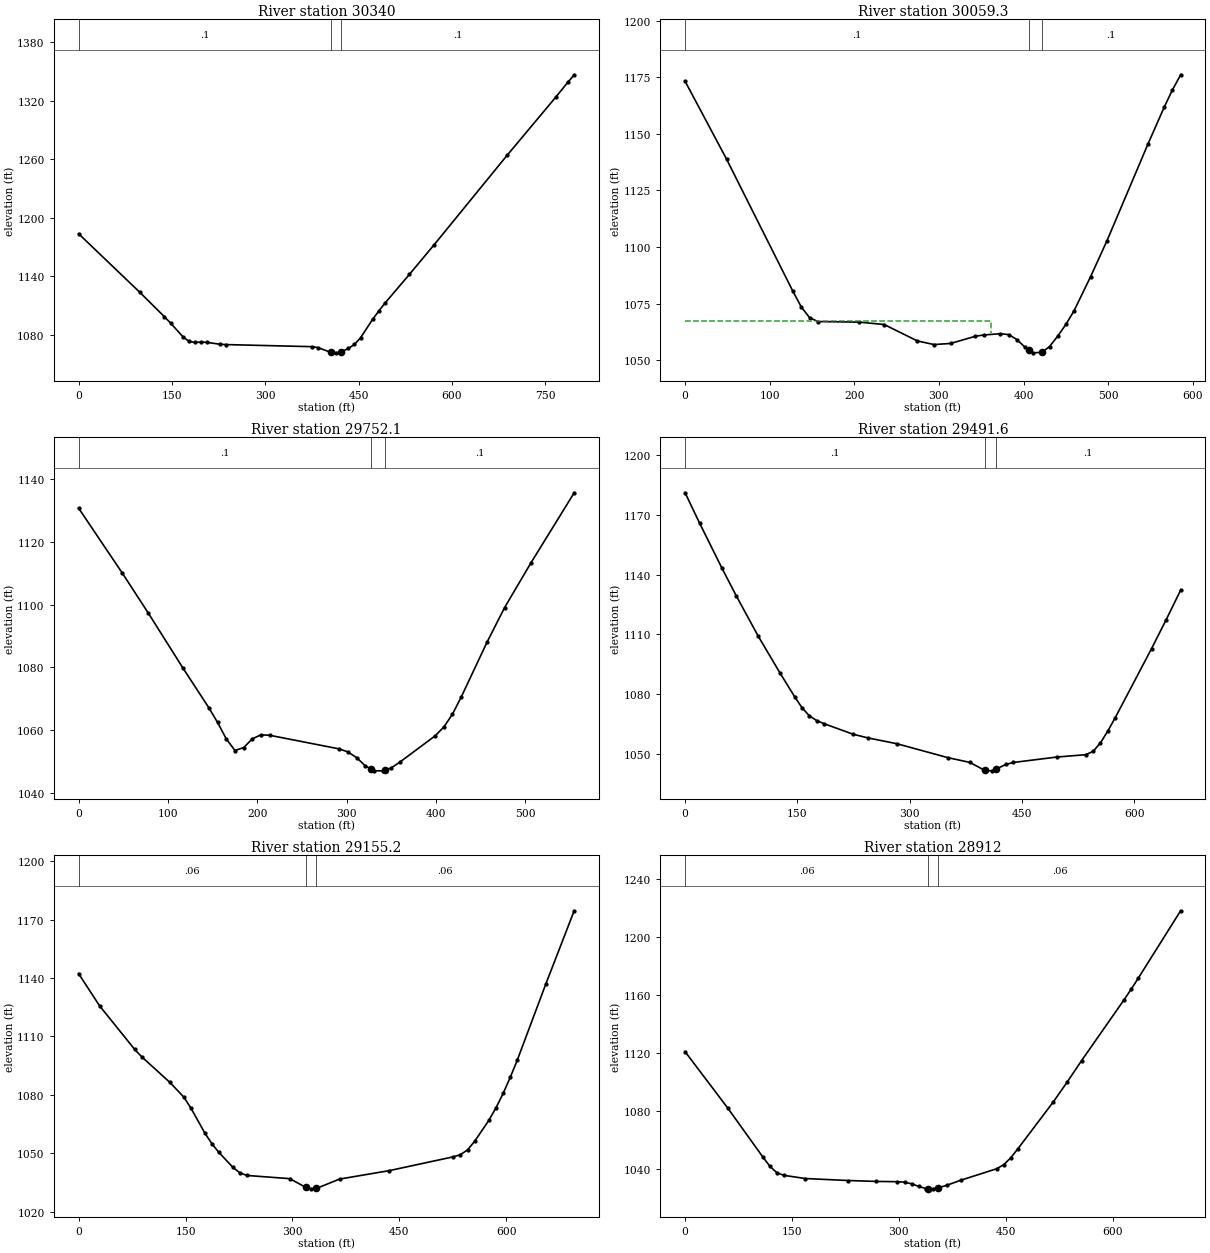
Type RM Length L Ch R = 1 ,30340   ,276.8,280.7,284.5
XS GIS Cut Line= 3
     1871425.896      389673.235     1871836.348      389619.521
     1872216.058      389571.836
#Sta/Elev= 30
       0 1183.42    98.6  1123.2     138 1098.26   147.8 1091.82   167.6  1077.8
   177.4    1073   187.3 1071.92   197.1 1072.36     207 1071.96   226.7 1070.11
   236.5 1069.73   374.5  1067.6   384.4 1066.68   404.1 1062.08   406.2 1061.91
     414 1061.26   421.2 1062.28   423.8 1062.65   433.6 1065.82   443.4 1069.86
   453.2 1076.73   472.8 1095.79   482.6 1104.21   492.4 1112.21   531.7 1141.71
     571 1171.76   688.7 1263.84   767.2 1323.73   786.8 1339.12   796.6 1346.53
#Mann= 3 , 0 , 0
       0      .1       0   406.2    .045       0   421.2      .1       0
Bank Sta=406.2,421.2
XS Rating Curve= 0 ,0
Exp/Cntr=0.3,0.1

Type RM Length L Ch R = 1 ,30059.3 ,300.5,307.2,313.9
XS GIS Cut Line= 3
     1871414.251       389827.92     1871790.429      389896.797
     1871993.485      389905.219
#Sta/Elev= 30
       0 1173.21      49 1138.81   127.5 1080.34   137.3  1073.5   147.1 1068.77
   156.9 1067.03   205.9 1066.79   235.3 1065.72   274.6 1058.46   294.2 1056.87
   313.8 1057.36   343.2 1060.54     353  1061.1   372.6 1061.66   382.4 1061.27
   392.1  1059.1   401.8 1055.67   406.8  1054.4   411.5 1053.21   421.8 1053.46
   430.8    1056   440.5 1060.63   450.2 1065.84   459.8 1071.85   479.2 1086.82
   498.6  1102.7     547  1145.4   566.3 1161.78     576 1169.38   585.7 1176.07
#Mann= 3 , 0 , 0
       0      .1       0   406.8    .045       0   421.8      .1       0
#XS Ineff= 2 , 0
          361.91 1067.21
Permanent Ineff=
       F       F
Bank Sta=406.8,421.8
XS Rating Curve= 0 ,0
Exp/Cntr=0.3,0.1

Type RM Length L Ch R = 1 ,29752.1 ,273.4,260.5,247.5
XS GIS Cut Line= 3
     1871398.356      390165.243     1871709.189      390177.606
     1871938.781      390258.846
#Sta/Elev= 30
       0 1130.73    48.6 1110.18    77.8  1097.4   116.6 1079.88   145.8 1067.14
   155.5 1062.49   165.3 1057.22     175 1053.55   184.7 1054.49   194.4 1057.28
   204.2 1058.56   213.9  1058.4   291.6 1054.07   301.4  1053.1   311.1 1051.28
   320.8 1048.68   327.5  1047.6   330.6  1047.1   340.3 1047.08   342.5  1047.3
     350 1048.04   359.8 1049.93   398.8 1058.18   408.5 1060.96   418.2 1065.03
     428 1070.47   457.2 1088.13   476.7 1099.06   505.9 1113.17   554.6 1135.64
#Mann= 3 , 0 , 0
       0      .1       0   327.5    .045       0   342.5      .1       0
Bank Sta=327.5,342.5
XS Rating Curve= 0 ,0
Exp/Cntr=0.3,0.1

Type RM Length L Ch R = 1 ,29491.6 ,341.8,336.4,331.1
XS GIS Cut Line= 4
     1871325.947      390488.438     1871656.206      390454.883
     1871854.009      390407.198     1871970.571      390357.748
#Sta/Elev= 30
       0 1181.18    19.5 1165.83    48.8 1143.62    68.3 1129.45    97.6 1109.19
   126.9 1090.56   146.4 1078.68   156.2 1073.18     166 1069.13   175.7 1066.75
   185.5 1065.19   224.6 1059.85   244.1 1058.04   283.1 1055.09   351.3 1048.08
   380.4 1045.72     400 1041.78   409.5 1041.48     415 1042.32   428.8 1044.72
   438.5 1045.68   496.7 1048.42   535.4 1049.59   545.2  1051.3   554.9 1055.55
   564.6  1061.4   574.4 1068.03   623.1 1102.85   642.6 1117.35     662 1132.25
#Mann= 3 , 0 , 0
       0      .1       0     400    .045       0     415      .1       0
Bank Sta=400,415
XS Rating Curve= 0 ,0
Exp/Cntr=0.3,0.1

Type RM Length L Ch R = 1 ,29155.2 ,239.9,243.2,246.4
XS GIS Cut Line= 3
     1871612.054      390868.148     1871806.324      390772.779
      1872228.42      390546.719
#Sta/Elev= 30
       0 1142.21    29.5 1125.67    78.7 1103.34    88.5 1099.58   127.9 1086.48
   147.6 1078.89   157.4 1073.33   177.1 1060.41   186.9 1055.01   196.7 1050.54
   216.4 1042.86   226.4 1039.95   236.4 1038.68   296.2 1037.05   318.7 1032.56
   326.2 1031.82   333.7 1032.05     366 1036.82   435.9 1041.17   525.6 1048.25
   535.6 1049.35   545.6  1051.8   555.6 1056.23   575.5 1066.95   585.5 1073.38
   595.5 1080.76   605.5    1089   615.4 1097.88   655.3 1136.81   695.2  1174.5
#Mann= 3 , 0 , 0
       0     .06       0   318.7    .045       0   333.7     .06       0
Bank Sta=318.7,333.7
XS Rating Curve= 0 ,0
Exp/Cntr=0.3,0.1

Type RM Length L Ch R = 1 ,28912   ,347,356.8,366.6
XS GIS Cut Line= 2
     1871744.511      391002.372     1872403.264      390779.844
#Sta/Elev= 30
       0 1121.01    59.6 1082.36   109.3 1048.34   119.2 1041.95   129.1 1037.51
   139.1 1035.82   168.9 1033.65   228.5  1032.3   268.2 1031.67     298 1031.48
   307.9 1031.12   317.9 1030.04   327.8 1028.21   337.7 1026.79   340.5 1026.73
   347.7 1026.56   355.5 1027.27   367.5 1029.08   387.4 1032.58   437.1 1040.38
     447 1043.15   456.9 1047.94   466.9 1054.13   516.5 1086.33   536.4 1100.32
   556.3 1114.85   615.9 1156.76   625.8 1163.97   635.7 1171.52   695.3 1218.06
#Mann= 3 , 0 , 0
       0     .06       0   340.5    .045       0   355.5     .06       0
Bank Sta=340.5,355.5
XS Rating Curve= 0 ,0
Exp/Cntr=0.3,0.1

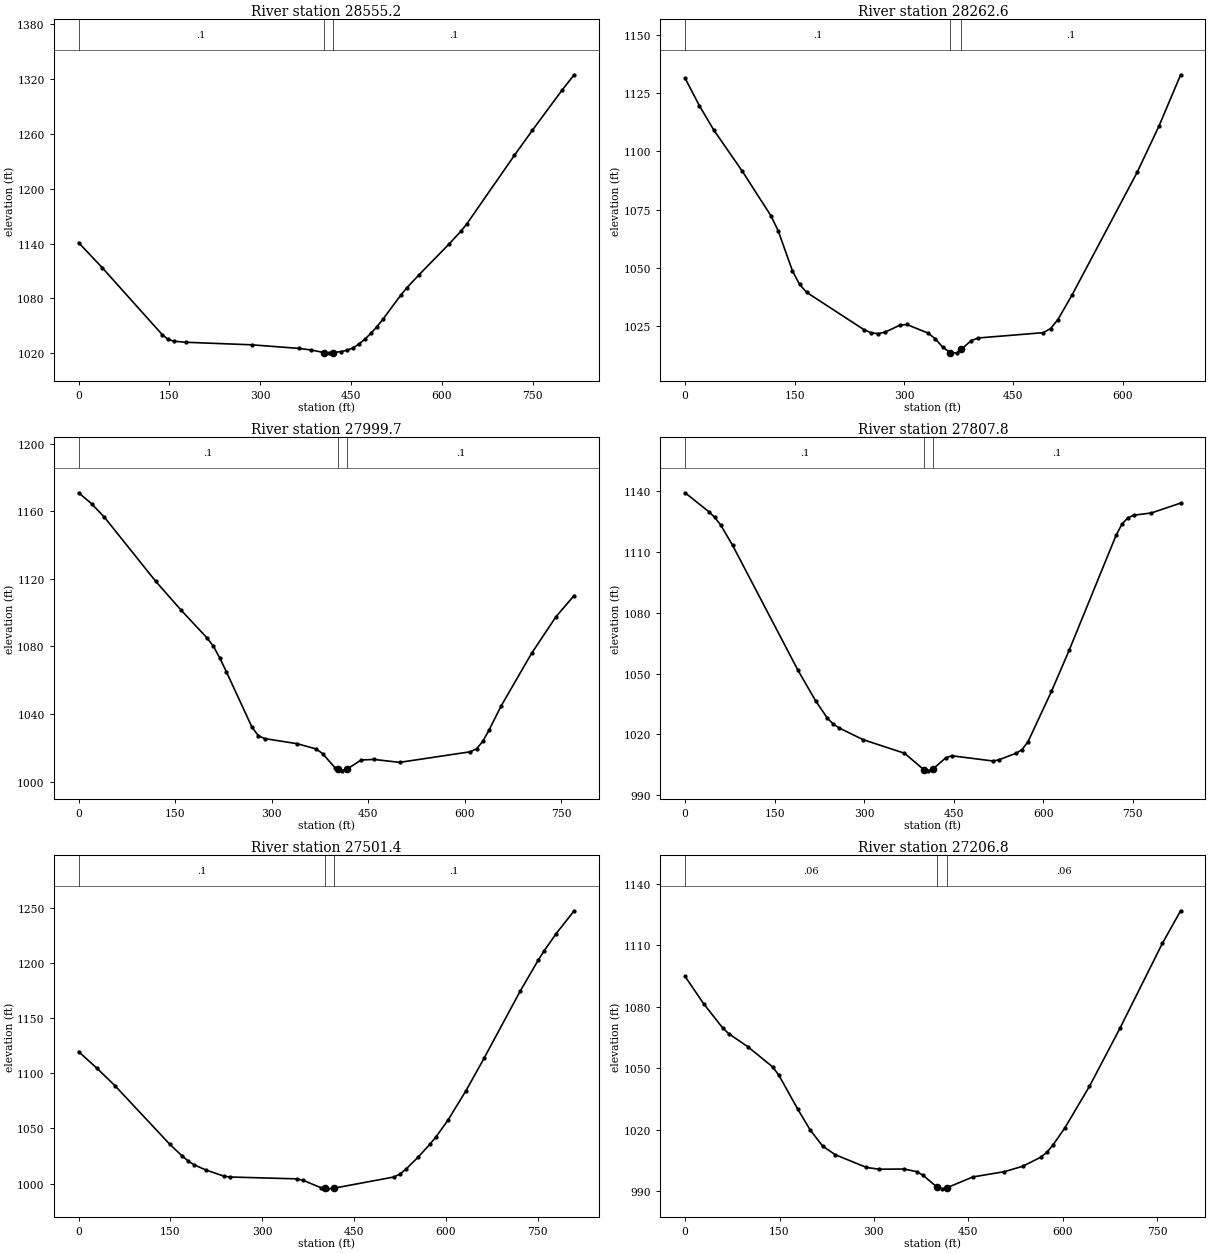
Type RM Length L Ch R = 1 ,28555.2 ,292.3,292.6,292.8
XS GIS Cut Line= 3
     1871707.863      391191.584     1872168.373      391240.794
     1872523.358      391235.496
#Sta/Elev= 30
       0 1140.93    39.4  1113.2     138 1040.18   147.8 1034.88   157.7 1032.92
   177.4  1031.8   285.8 1029.01   364.6 1025.04   384.3 1023.27   404.9 1020.55
   413.9 1020.22   419.9 1020.53   433.6 1021.63   443.4 1023.03   453.3 1025.68
   463.1 1029.96     473 1035.47   482.9  1041.8   492.7 1049.02   502.6 1057.14
   532.2  1083.7     542 1091.54   561.8 1105.57   611.1 1139.05   630.8 1153.19
   640.6 1161.17   719.5 1236.57   749.1 1263.96   798.4 1308.21   818.2 1324.86
#Mann= 3 , 0 , 0
       0      .1       0   404.9    .045       0   419.9      .1       0
Bank Sta=404.9,419.9
XS Rating Curve= 0 ,0
Exp/Cntr=0.3,0.1

Type RM Length L Ch R = 1 ,28262.6 ,264.5,262.9,261.3
XS GIS Cut Line= 3
     1871714.487      391480.983     1872113.624      391528.667
     1872387.369      391484.515
#Sta/Elev= 30
       0 1131.29    19.6 1119.53    39.2 1109.16    78.4 1091.45   117.6  1072.4
   127.5    1066   147.1 1048.81   156.9 1042.95   166.7 1039.52   245.1 1023.57
   254.9  1022.2   264.7 1021.83   274.5 1022.53   294.1 1025.42   303.9 1025.78
   333.4 1022.03   343.2 1019.55     353 1016.11   363.8 1013.65   372.6 1013.62
   378.8 1015.18   392.2 1018.86     402 1019.99   491.1 1022.27     501 1024.04
   510.9 1027.79   530.7 1038.55   619.8 1091.06   649.6  1110.8   679.3 1132.78
#Mann= 3 , 0 , 0
       0      .1       0   363.8    .045       0   378.8      .1       0
Bank Sta=363.8,378.8
XS Rating Curve= 0 ,0
Exp/Cntr=0.3,0.1

Type RM Length L Ch R = 1 ,27999.7 ,204,192.1,184.4
XS GIS Cut Line= 3
     1871636.973      391766.324     1872254.844      391795.033
     1872399.731        391839.5
#Sta/Elev= 30
       0 1170.98      20 1164.55    39.9 1156.59   119.7 1118.59   159.6 1101.35
   199.5 1085.06   209.5 1080.08   219.5 1073.05   229.5  1065.1   269.4 1032.21
   279.3 1027.14   289.3 1025.44   339.2 1022.45   369.1 1019.32   379.1 1016.56
   399.1 1007.92   402.3 1007.42     409 1006.36   417.3 1007.41     439 1012.78
   458.9 1013.11   498.8 1011.38   608.6 1017.64   618.5 1019.42     628 1023.81
   637.5 1030.26   656.4 1044.64   703.8 1075.84   741.7 1097.54   770.1 1110.16
#Mann= 3 , 0 , 0
       0      .1       0   402.3    .045       0   417.3      .1       0
Bank Sta=402.3,417.3
XS Rating Curve= 0 ,0
Exp/Cntr=0.3,0.1

Type RM Length L Ch R = 1 ,27807.8 ,303.1,306.2,305
XS GIS Cut Line= 3
     1871703.254      392162.223     1872062.738      391971.112
     1872466.953       391847.27
#Sta/Elev= 30
       0 1139.26    39.7 1129.92    49.6 1127.12    59.6 1123.34    79.4 1113.39
   188.7 1051.79   218.5 1036.55   238.3 1027.92   248.2 1025.03   258.2 1023.08
   297.9 1017.35   367.4 1010.62   399.6 1002.57   407.1 1001.93   414.6 1002.74
   436.6 1008.37   446.4 1009.38   515.3  1006.8   525.1 1007.32   554.6 1010.66
   564.4 1012.44   574.3 1016.33   613.6  1041.2   643.1 1061.41   721.7 1118.19
   731.6  1123.8   741.4 1126.86   751.2 1128.18   780.7 1129.28   829.9 1134.17
#Mann= 3 , 0 , 0
       0      .1       0   399.6    .045       0   414.6      .1       0
Bank Sta=399.6,414.6
XS Rating Curve= 0 ,0
Exp/Cntr=0.3,0.1

Type RM Length L Ch R = 1 ,27501.4 ,295.9,294.6,293.3
XS GIS Cut Line= 3
     1871802.089      392386.287     1872295.532      392208.613
     1872537.487      392058.495
#Sta/Elev= 30
       0 1119.66    29.7 1104.75    59.4 1088.78   148.4  1035.9   168.2 1025.46
   178.1 1020.87     188 1017.18   207.8 1012.31   237.5 1006.68   247.4 1005.95
   356.2 1004.26   366.1 1003.04   395.8  996.21   401.9  995.59   405.7  995.21
   416.9   995.8   514.6 1005.93   524.5 1008.58   534.3    1013   553.9 1023.69
   573.6 1035.65   583.4 1042.19     603 1057.42   632.5 1084.22   661.9 1113.57
   720.8 1174.34   750.3 1202.52   760.1 1211.08   779.7 1226.72   809.2 1247.51
#Mann= 3 , 0 , 0
       0      .1       0   401.9    .045       0   416.9      .1       0
Bank Sta=401.9,416.9
XS Rating Curve= 0 ,0
Exp/Cntr=0.3,0.1

Type RM Length L Ch R = 1 ,27206.8 ,167.1,169.6,172.1
XS GIS Cut Line= 3
     1871924.198      392679.373     1872399.731      392477.059
     1872629.324      392334.006
#Sta/Elev= 30
       0 1094.83    29.8 1081.37    59.6 1069.73    69.6  1066.8    99.4 1060.58
   139.1 1050.65   149.1 1046.53   178.9 1030.04   198.8 1019.83   218.6 1011.95
   238.5 1007.78   288.2 1001.54   308.1 1000.69   347.8 1000.78   367.7   999.5
   377.6  997.83   400.4  991.89   407.5   991.1   415.4  991.56   457.2  996.91
   506.8  999.46   536.1 1002.08   565.1 1006.54   574.8 1008.95   584.4 1012.46
   603.7 1021.04   642.4 1041.15   690.7 1069.42   758.3    1111   787.3  1126.9
#Mann= 3 , 0 , 0
       0     .06       0   400.4    .045       0   415.4     .06       0
Bank Sta=400.4,415.4
XS Rating Curve= 0 ,0
Exp/Cntr=0.3,0.1

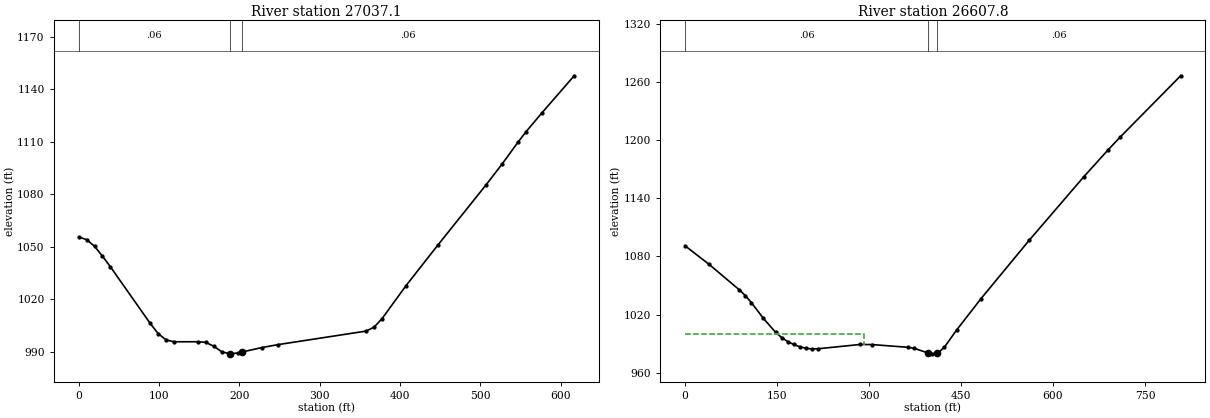
Type RM Length L Ch R = 1 ,27037.1 ,422,429.4,435.7
XS GIS Cut Line= 3
     1872178.403      392746.412     1872325.606      392688.332
     1872764.767      392556.699
#Sta/Elev= 30
       0 1055.54     9.9 1054.04    19.8 1050.25    29.7 1044.56    39.6 1038.49
      89 1006.24    98.9 1000.42   108.8  996.78   118.7  995.71   148.4  995.72
   158.2  995.39   168.2  993.13   178.2  989.99   188.2  988.82   188.5  988.84
   198.1  989.32   203.5  989.89     228  992.39     248  994.07   357.6  1001.8
   367.6 1004.02   377.5 1008.85   407.4 1027.73   447.3 1051.06   507.1 1085.32
     527 1097.19   546.9 1109.73   556.9  1115.7   576.8 1126.53   616.7 1147.58
#Mann= 3 , 0 , 0
       0     .06       0   188.5    .045       0   203.5     .06       0
Bank Sta=188.5,203.5
XS Rating Curve= 0 ,0
Exp/Cntr=0.3,0.1

Type RM Length L Ch R = 1 ,26607.8 ,316.1,312.2,309.4
XS GIS Cut Line= 3
     1872094.197      393063.402      1872497.09      393079.295
     1872902.038      393075.036
#Sta/Elev= 30
       0 1090.95    39.3 1071.73    88.5 1045.49    98.3 1039.52   108.2 1032.23
   127.8 1015.98   147.5 1001.73   157.4  996.27   167.2  992.16     177  989.08
   186.8  986.75   196.7   985.2   206.5  984.53   216.4  984.64   285.2  989.08
   304.9     989   363.9  986.16   373.7  985.13   395.7  980.42   403.2  979.43
   410.7  980.35   413.1  980.65     423   986.4   442.7 1003.91   482.2 1036.09
   561.2 1096.65   650.1 1162.15   689.6 1189.82   709.4 1203.08   808.2 1266.51
#Mann= 3 , 0 , 0
       0     .06       0   395.7    .045       0   410.7     .06       0
#XS Ineff= 2 , 0
          291.41  999.73
Permanent Ineff=
       F       F
Bank Sta=395.7,410.7
XS Rating Curve= 0 ,0
Exp/Cntr=0.3,0.1