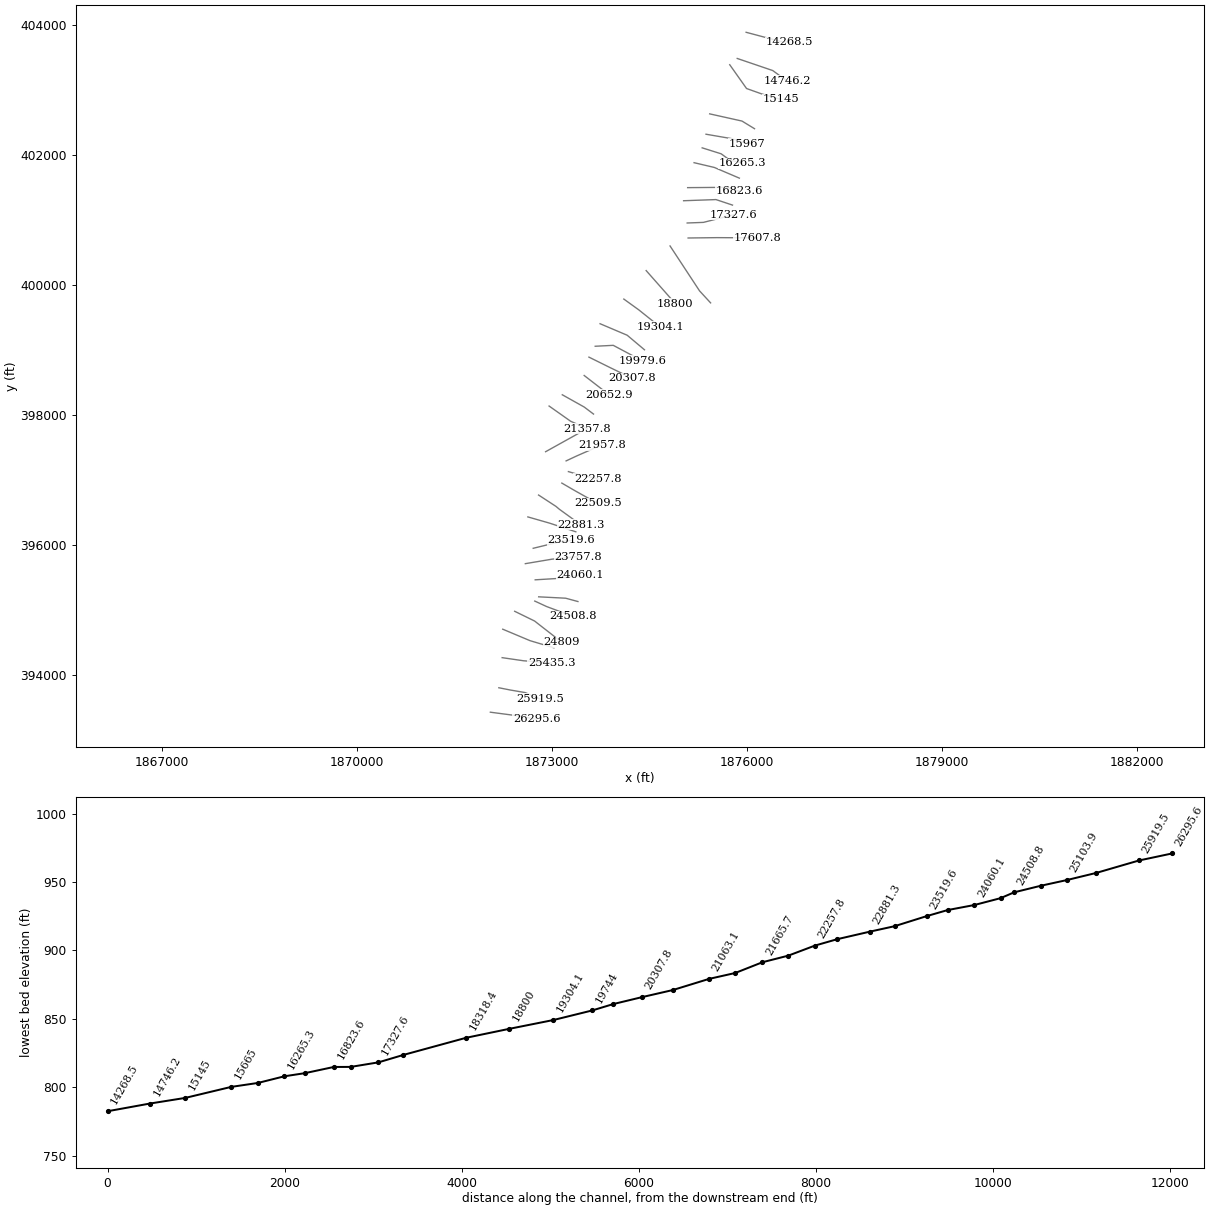
HEC-RAS study ArmstrngCk.prj: ArmstrngCk

--- ArmstrngCk.g01 (geometry) --- (continued)

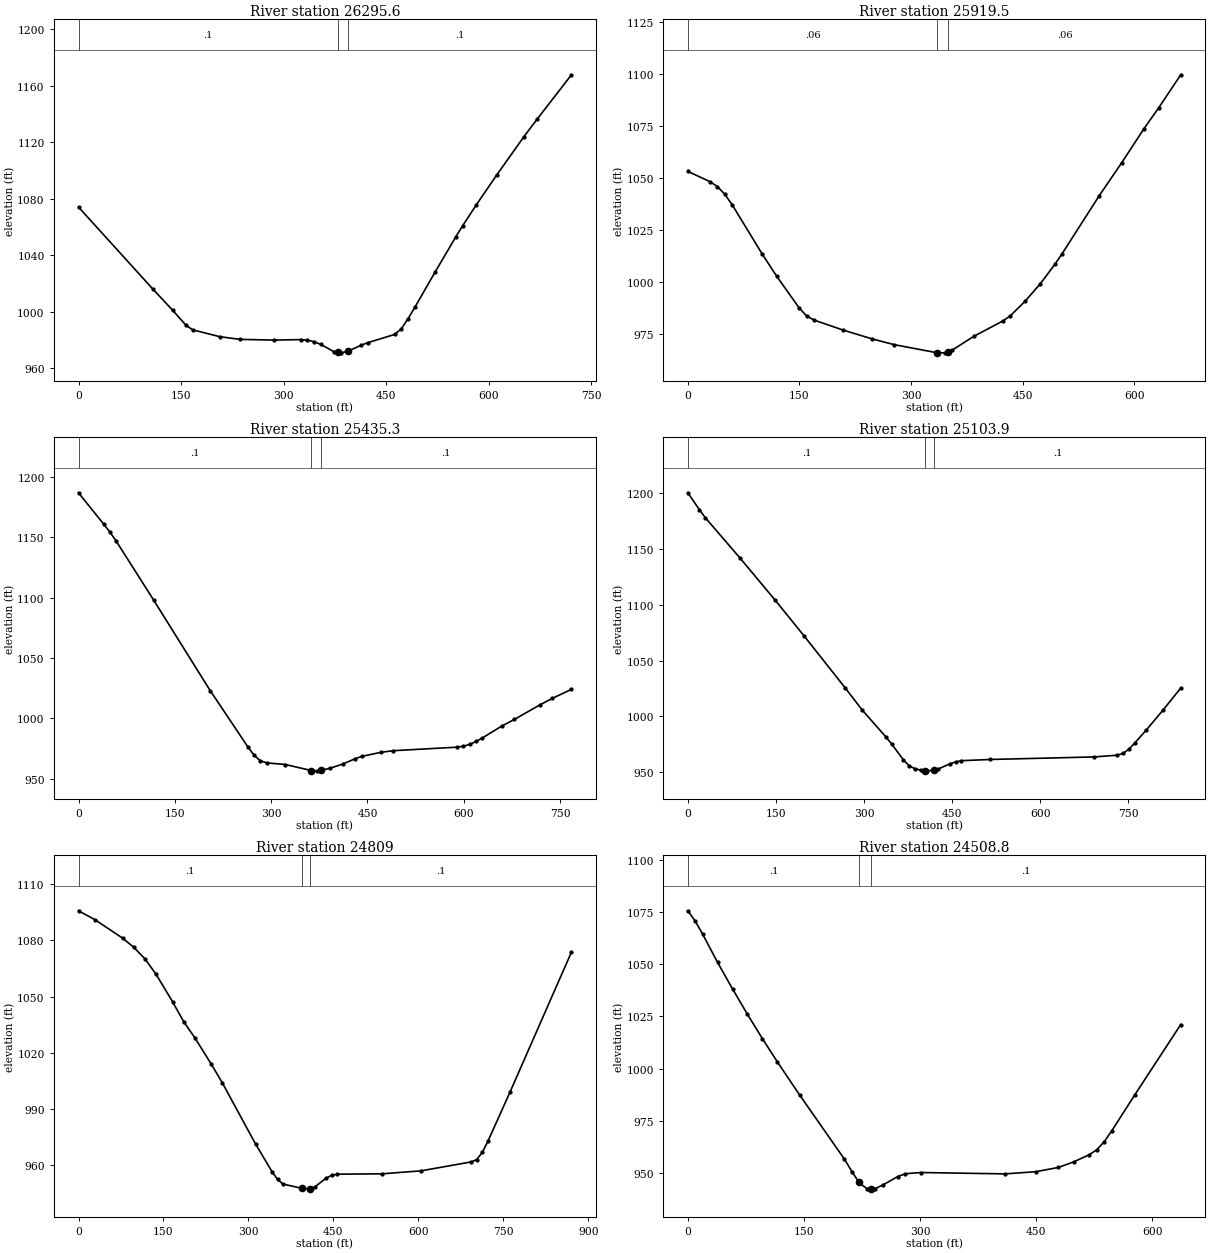
Type RM Length L Ch R = 1 ,26295.6 ,376.9,376.1,375.3
XS GIS Cut Line= 3
     1872048.279       393430.75     1872516.294      393368.937
     1872760.014      393319.486
#Sta/Elev= 30
       0 1074.03   108.2 1016.29   137.7    1001   157.4  990.25   167.2  987.13
   206.5  982.33     236   980.4   285.2  979.91   324.6  980.24   334.4  979.88
   344.2   978.8   354.1  976.87   373.7  971.64   378.7  971.26   383.6  970.88
   393.7  971.95   413.1  976.22   422.9  978.05   462.2   983.9   472.1  987.92
     482  995.18     492 1003.31   521.8 1028.39   551.7 1052.98   561.6 1060.73
   581.5 1075.52   611.3 1096.59   651.1 1123.74     671 1136.53   720.8 1167.66
#Mann= 3 , 0 , 0
       0      .1       0   378.7    .045       0   393.7      .1       0
Bank Sta=378.7,393.7
XS Rating Curve= 0 ,0
Exp/Cntr=0.3,0.1

Type RM Length L Ch R = 1 ,25919.5 ,482.1,484.1,486.2
XS GIS Cut Line= 4
     1872178.992      393806.722     1872355.065      393772.003
     1872585.697      393732.324     1872813.848      393633.128
#Sta/Elev= 30
       0 1053.21    29.9 1048.21    39.9 1045.85    49.8  1042.1    59.8 1036.99
    99.7  1013.5   119.6 1002.56   149.6  987.37   159.5  983.55   169.5  981.52
   208.7  976.68   247.7  972.43     277  969.68     335  965.74   335.5  965.71
   345.2  965.76     350  966.35     355  966.96   384.2  973.66   423.4  981.09
   433.4  983.58   453.3  990.65   473.2  998.84   493.1 1008.34     503 1013.56
   552.8 1041.48   582.7 1057.21   612.5 1073.57   632.4  1083.7   662.3 1099.75
#Mann= 3 , 0 , 0
       0     .06       0     335    .045       0     350     .06       0
Bank Sta=335,350
XS Rating Curve= 0 ,0
Exp/Cntr=0.3,0.1

Type RM Length L Ch R = 1 ,25435.3 ,338.7,331.4,324.2
XS GIS Cut Line= 3
     1872230.186      394269.644      1872558.68       394221.96
     1872993.139      394188.404
#Sta/Elev= 30
       0  1186.9      39  1161.1    48.8 1154.39    58.6 1146.96   117.2 1097.88
     205 1023.12   263.6  976.56   273.4  969.54   283.1     965   292.9  963.22
   322.2  961.84   362.5  956.85   371.6   956.6   377.5  956.96   391.4  958.72
   411.2  962.15     431  966.68   440.9  968.52   470.6  971.91   490.4   973.3
   589.4   976.2   599.3  976.96   609.2  978.53   619.1  980.91     629  983.86
   658.8  993.58   678.6  999.14   718.2 1011.14     738 1016.67   767.7 1024.09
#Mann= 3 , 0 , 0
       0      .1       0   362.5    .045       0   377.5      .1       0
Bank Sta=362.5,377.5
XS Rating Curve= 0 ,0
Exp/Cntr=0.3,0.1

Type RM Length L Ch R = 1 ,25103.9 ,301,294.9,288.8
XS GIS Cut Line= 3
     1872239.017      394707.635     1872659.347      394531.026
     1873026.695      394421.528
#Sta/Elev= 30
       0 1199.99    19.8 1184.86    29.7 1177.79    89.2 1141.46   148.7    1104
   198.2 1071.89   267.6 1025.78   297.3 1005.52     337  981.87   346.9  975.49
   366.7  961.48   376.6     956   386.6  953.32   396.5  952.02   404.4  951.53
   406.4   951.4   419.4  952.06   426.2  953.03     446  957.59   455.9  959.38
   465.8  960.49   514.9  961.56   691.8  963.84   731.1  965.39     741  966.97
   750.8  970.73   760.6  976.08   780.3  987.78   809.8  1006.2   839.2 1025.44
#Mann= 3 , 0 , 0
       0      .1       0   404.4    .045       0   419.4      .1       0
Bank Sta=404.4,419.4
XS Rating Curve= 0 ,0
Exp/Cntr=0.3,0.1

Type RM Length L Ch R = 1 ,24809   ,293.2,300.2,307.2
XS GIS Cut Line= 4
     1872422.691      394983.146     1872729.926      394832.946
     1872797.102      394780.045     1873146.789      394508.067
#Sta/Elev= 30
       0 1095.89    29.3 1091.08    78.2 1081.19    97.7 1076.34   117.2 1070.23
   136.8 1062.02   166.1 1047.26   185.6 1036.66   205.2  1028.1   234.5 1013.86
     254 1003.88   312.7  971.16     342  956.26   351.5  952.24     361  949.78
   394.5  947.49   408.5  947.22   409.5  947.35     418  948.41   437.3  952.96
   447.2  954.44     457  955.06   535.8  955.25   604.7  956.84   693.3  961.61
   703.1  962.84     713  966.71   722.8  972.56   762.2  999.11   870.5 1073.84
#Mann= 3 , 0 , 0
       0      .1       0   394.5    .045       0   409.5      .1       0
Bank Sta=394.5,409.5
XS Rating Curve= 0 ,0
Exp/Cntr=0.3,0.1

Type RM Length L Ch R = 1 ,24508.8 ,147,153.9,160.8
XS GIS Cut Line= 3
     1872731.757      395140.328     1872915.431      395055.556
     1873322.646      394903.447
#Sta/Elev= 30
       0  1075.5     9.6 1070.59    19.3 1064.25    38.5  1050.8    57.8 1038.11
    77.1 1025.96    96.3 1014.38   115.6 1003.28   144.5  987.36   202.3  956.71
   212.2  950.61   221.1  945.65     222  945.15   231.9  942.44   236.1  942.47
   241.8  942.51   251.7   944.2   271.4  948.34   281.3  949.68   301.1  950.25
   409.8   949.6   449.3  950.63   478.9  952.68   498.7  955.34   518.4  958.71
   528.3  961.09   538.2  965.02   548.1  970.35   577.7  987.48     637 1021.08
#Mann= 3 , 0 , 0
       0      .1       0   221.1    .045       0   236.1      .1       0
Bank Sta=221.1,236.1
XS Rating Curve= 0 ,0
Exp/Cntr=0.3,0.1

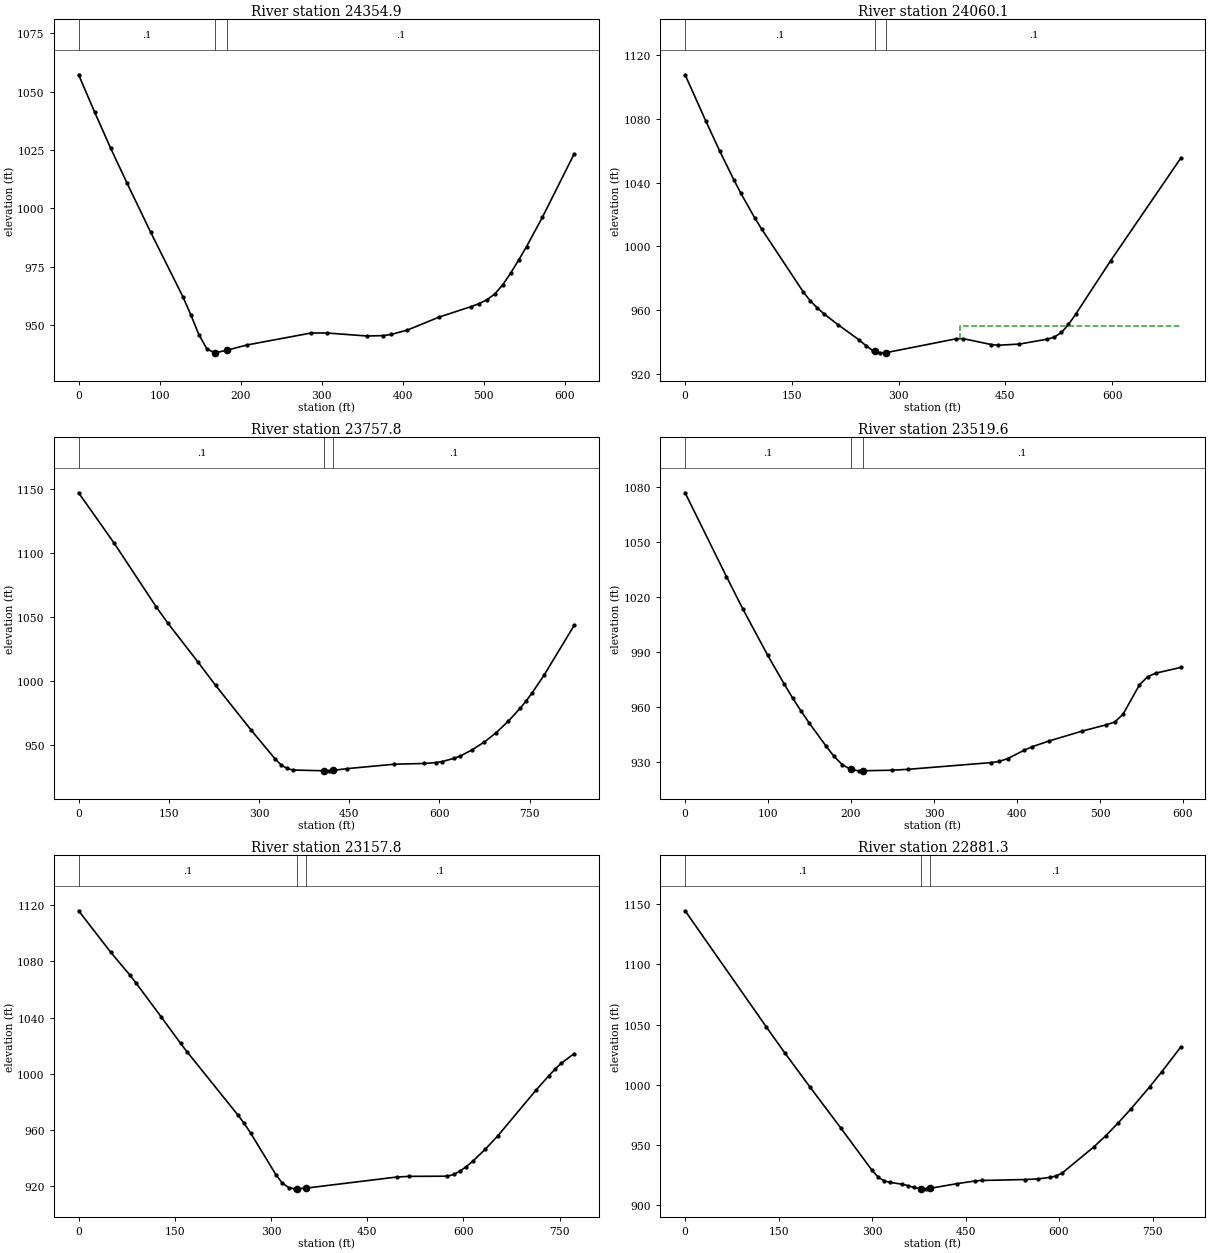
Type RM Length L Ch R = 1 ,24354.9 ,292.3,294.8,297.3
XS GIS Cut Line= 3
     1872791.804      395205.674     1873206.836      395184.481
     1873395.808      395133.264
#Sta/Elev= 30
       0 1057.16    19.8 1041.13    39.6 1025.67    59.4 1011.02      89  989.69
   128.6   962.2   138.5  954.35   148.4  945.93   158.3   939.8   167.9  938.21
   168.2  938.16   182.9  939.27   207.8  941.54   286.9  946.65   306.7  946.64
   356.2  945.36     376  945.54   385.9  946.05   405.7  947.92   444.9  953.48
   484.1  957.93   493.9  959.21   503.7  960.85   513.5  963.37   523.3  967.28
     533  972.28   542.8  977.79   552.6  983.64   572.2  996.18   611.4 1023.31
#Mann= 3 , 0 , 0
       0      .1       0   167.9    .045       0   182.9      .1       0
Bank Sta=167.9,182.9
XS Rating Curve= 0 ,0
Exp/Cntr=0.3,0.1

Type RM Length L Ch R = 1 ,24060.1 ,299.9,302.3,303.2
XS GIS Cut Line= 3
     1872738.527       395467.35     1873089.391      395488.543
     1873430.836      395535.639
#Sta/Elev= 30
       0  1107.7    29.3  1078.5    48.8 1059.69    68.4 1041.88    78.1  1033.5
    97.6 1018.05   107.4 1010.98     166  971.42   175.8  965.92   185.5  961.45
   195.3   957.6   214.8  950.84   244.1  941.39   253.9  937.75   263.6  934.63
   267.3  934.08   273.4  933.17   282.3  933.28     381     942   390.9  942.05
   430.3  938.37   440.1  937.94   469.7  938.68   509.1  941.77   518.9  943.07
   528.8  945.98   538.6  950.96   548.5  957.25   597.7  990.89   696.2 1055.26
#Mann= 3 , 0 , 0
       0      .1       0   267.3    .045       0   282.3      .1       0
#XS Ineff= 2 , 0
                          386.89          950.03
Permanent Ineff=
       F       F
Bank Sta=267.3,282.3
XS Rating Curve= 0 ,0
Exp/Cntr=0.3,0.1

Type RM Length L Ch R = 1 ,23757.8 ,237.3,238.2,240.6
XS GIS Cut Line= 3
     1872586.742      395715.949      1872996.75      395784.884
     1873403.118      395825.521
#Sta/Elev= 30
       0 1147.21    59.4 1107.53   128.7 1058.11   148.5 1045.08     198 1014.97
   227.7  996.48   287.1  961.28   326.7  938.87   336.6  934.17   346.5  931.36
   356.4  930.11   408.3  929.53   415.8  929.48   423.3  929.81   445.6  931.17
   525.3  934.68   575.1  935.24   595.1  936.01     605  936.79   624.9  939.33
   634.9  941.06   654.8  946.04   674.7  951.99   694.7  959.48   714.6  968.33
   734.5  978.52   744.5  984.33   754.4  990.62   774.4 1004.59   824.2 1043.38
#Mann= 3 , 0 , 0
       0      .1       0   408.3    .045       0   423.3      .1       0
Bank Sta=408.3,423.3
XS Rating Curve= 0 ,0
Exp/Cntr=0.3,0.1

Type RM Length L Ch R = 1 ,23519.6 ,372.9,361.5,349
XS GIS Cut Line= 3
     1872707.915      395952.437     1873124.109      396054.012
     1873291.903      396072.531
#Sta/Elev= 30
       0    1077    49.8 1031.24    69.7 1013.41    99.6  988.13   119.6  972.34
   129.5  964.87   139.5  957.87   149.4  951.27   169.4  938.82   179.3  933.06
   189.3  928.45   199.6  925.77   209.2  925.02   214.6  925.07   249.1  925.36
     269  925.86   368.6  929.52   378.6  930.18   388.6  931.68   408.5  936.25
   418.4   938.2   438.3   941.3   478.1   946.7   507.8  950.21   517.8  951.72
   527.7  955.91   547.6  972.02   557.5  976.49   567.4  978.43   597.2  981.52
#Mann= 3 , 0 , 0
       0      .1       0   199.6    .045       0   214.6      .1       0
Bank Sta=199.6,214.6
XS Rating Curve= 0 ,0
Exp/Cntr=0.3,0.1

Type RM Length L Ch R = 1 ,23157.8 ,285.9,276.6,270
XS GIS Cut Line= 3
     1872625.497      396435.169     1872959.657      396339.347
     1873363.228      396206.196
#Sta/Elev= 30
       0  1116.2    49.7 1086.79    79.5 1070.49    89.4 1064.69   129.1 1040.23
   158.9 1021.54   168.8 1015.67   248.3  970.38   258.2  964.33   268.2  957.46
   307.9  927.54   317.8  921.68   327.8  918.53   337.7  917.68   340.1  917.72
   355.1  918.23   495.9  926.11   515.6  926.59   574.9  926.71   584.8  927.94
   594.7  930.38   604.6   933.6   614.5   937.4   634.2  946.05     654  955.74
   713.3  988.26   733.1  998.41     743 1003.28   752.8 1007.45   772.6 1014.24
#Mann= 3 , 0 , 0
       0      .1       0   340.1    .045       0   355.1      .1       0
Bank Sta=340.1,355.1
XS Rating Curve= 0 ,0
Exp/Cntr=0.3,0.1

Type RM Length L Ch R = 1 ,22881.3 ,367.9,371.8,374.2
XS GIS Cut Line= 4
     1872790.332      396771.904     1873058.135      396596.888
     1873108.509      396554.346     1873439.986      396314.313
#Sta/Elev= 30
       0 1144.39     130 1048.29     160 1026.47     200  998.44   249.9  964.14
   299.9  929.13   309.9  923.38   319.9  920.15   329.3   919.1   348.2  917.54
   357.6  916.41     367  914.88   378.7  913.89   385.8  913.73   393.7   914.2
   435.8  917.99   465.7   920.3   475.7  920.66   545.6  921.45   565.5  921.93
   585.5  923.26   595.5  924.41   605.5  927.05   655.4  948.32   675.3  957.94
   695.3  968.63   715.3  980.01   745.2  998.21   765.2 1011.05   795.1 1031.25
#Mann= 3 , 0 , 0
       0      .1       0   378.7    .045       0   393.7      .1       0
Bank Sta=378.7,393.7
XS Rating Curve= 0 ,0
Exp/Cntr=0.3,0.1

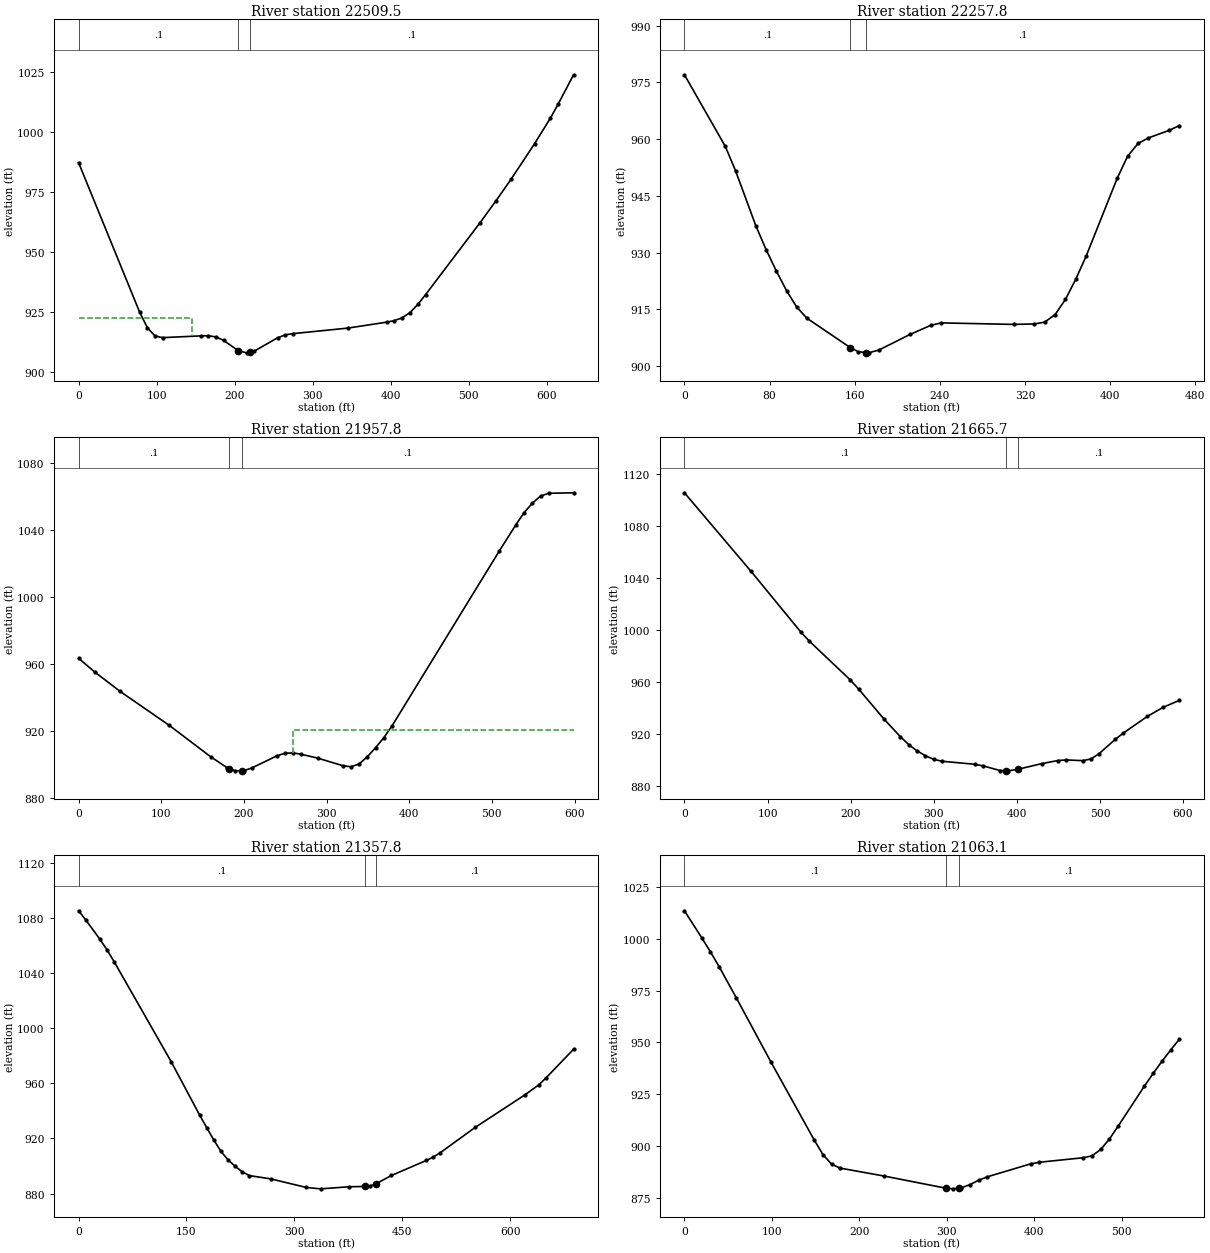
Type RM Length L Ch R = 1 ,22509.5 ,246.3,251.7,258.8
XS GIS Cut Line= 3
     1873148.261      396955.578     1873342.914      396842.286
     1873700.199      396642.206
#Sta/Elev= 30
       0  987.31    78.3  925.08    88.1  918.66    97.9   915.2   107.7  914.51
   156.7  915.24   166.5  915.27   176.3  914.81     186  913.34   204.6   909.1
   215.4  908.18   219.6  908.48   225.2  908.88   255.2  914.45   265.2  915.66
   275.2  916.18   345.1  918.47     395  920.94     405   921.6     415  922.79
     425  924.94     435  928.32     445  932.43   514.9  962.38   534.8  971.26
   554.8  980.54   584.8  995.28   604.8 1005.73   614.7 1011.54   634.7 1023.89
#Mann= 3 , 0 , 0
       0      .1       0   204.6    .045       0   219.6      .1       0
#XS Ineff= 2 , 0
           145.7  922.71
Permanent Ineff=
       F       F
Bank Sta=204.6,219.6
XS Rating Curve= 0 ,0
Exp/Cntr=0.3,0.1

Type RM Length L Ch R = 1 ,22257.8 ,283.6,300,314
XS GIS Cut Line= 3
     1873249.517      397132.187      1873406.12      397086.045
     1873701.637      397023.867
#Sta/Elev= 30
       0  977.03    38.4   958.1      48  951.68    67.2  937.03    76.8  930.76
    86.4  925.12      96  919.93   105.6  915.56   115.2  912.64   155.8   904.9
   163.3  903.81   170.8  903.57     173   903.5   182.7  904.23     212  908.36
   231.4  910.76   241.2  911.42   309.4  911.02   328.9  911.14   338.6  911.62
   348.4  913.63   358.1  917.63   367.8  922.96   377.6  929.11   406.8  949.71
   416.5  955.47   426.3  958.86     436  960.33   455.5  962.32   465.2  963.61
#Mann= 3 , 0 , 0
       0      .1       0   155.8    .045       0   170.8      .1       0
Bank Sta=155.8,170.8
XS Rating Curve= 0 ,0
Exp/Cntr=0.3,0.1

Type RM Length L Ch R = 1 ,21957.8 ,290.6,292.2,294.3
XS GIS Cut Line= 3
     1873214.195      397297.022     1873386.043      397377.242
     1873760.858      397541.222
#Sta/Elev= 30
       0  963.32      20  954.97    49.9   943.7   109.8  923.26   159.7  904.61
   179.7  898.03   182.2  897.56   189.6  896.17   197.2  896.21   199.6  896.22
   209.6  897.89   239.5  905.04   249.5  906.64   259.5  906.89   269.5  906.04
   289.4  903.74   319.4  899.27   329.4  898.58   339.3  900.24   349.3  904.57
   359.3  910.01   369.3  915.98   379.2  923.02     509 1027.44   528.9 1042.94
   538.9 1050.23   548.9 1055.88   558.8 1060.15   568.8 1061.82   598.8 1062.12
#Mann= 3 , 0 , 0
       0      .1       0   182.2    .045       0   197.2      .1       0
#XS Ineff= 2 , 0
                          258.81          920.48
Permanent Ineff=
       F       F
Bank Sta=182.2,197.2
XS Rating Curve= 0 ,0
Exp/Cntr=0.3,0.1

Type RM Length L Ch R = 1 ,21665.7 ,333,307.7,286.5
XS GIS Cut Line= 3
     1872898.653       397438.31     1873317.806      397671.434
     1873419.062      397727.949
#Sta/Elev= 30
       0 1105.71    79.9 1045.33   139.9  998.47   149.9  991.58   199.8  961.27
   209.8  954.26   239.8  931.52   259.8   917.7   269.8  911.62   279.8  906.78
   289.8  903.04   299.8  900.24   309.8  898.75   349.7  896.39   359.7  895.13
   379.7  891.61   386.5  891.43   389.7  891.35   401.5  892.58   429.7  896.88
   449.6  899.32   459.6  899.75   479.6  899.21   489.3  900.55     499  904.61
   518.3  915.56   527.9  920.37   556.9  933.27   576.2  940.37   595.6  945.69
#Mann= 3 , 0 , 0
       0      .1       0   386.5    .045       0   401.5      .1       0
Bank Sta=386.5,401.5
XS Rating Curve= 0 ,0
Exp/Cntr=0.3,0.1

Type RM Length L Ch R = 1 ,21357.8 ,292.3,294.6,292.9
XS GIS Cut Line= 3
     1872952.125      398141.007     1873283.681      397907.054
     1873541.511      397791.529
#Sta/Elev= 30
       0 1085.16     9.9 1078.55    29.7  1064.5    39.6 1056.75    49.5 1048.15
   128.7  975.74   168.2  937.08   178.2  927.81     188  918.92     198  910.64
   207.8  904.52   217.7  899.83   227.6  895.82   237.5  893.08   267.2   890.7
   316.7  884.48   336.5  883.48   376.1  884.98   398.3  885.21   405.8  885.57
   413.3  887.07     435  893.16   483.7  904.09   493.5  906.58   503.2  909.78
   551.9  928.19   620.1  951.45   639.6  958.76   649.4  963.62   688.3  984.75
#Mann= 3 , 0 , 0
       0      .1       0   398.3    .045       0   413.3      .1       0
Bank Sta=398.3,413.3
XS Rating Curve= 0 ,0
Exp/Cntr=0.3,0.1

Type RM Length L Ch R = 1 ,21063.1 ,414,409.8,405.6
XS GIS Cut Line= 3
     1873155.325      398314.292      1873492.06      398125.909
     1873635.702      398017.589
#Sta/Elev= 30
       0 1013.64    19.8 1000.56    29.7  993.79    39.6  986.66    59.4  971.47
    98.9   940.5   148.4  902.77   158.3  895.78   168.2  891.11   178.1   889.2
   227.6  885.43   298.6  879.52   306.7  879.19   313.6  879.55   316.6   879.7
   326.5  881.27   336.4  883.35   346.3  885.02   395.8  891.27   405.8  892.05
   455.8  894.23   465.8  895.13   475.8  898.22   485.8  903.28   495.8  909.53
   525.8  928.87   535.8  934.99   545.8  940.82   555.8  946.32   565.8  951.56
#Mann= 3 , 0 , 0
       0      .1       0   298.6    .045       0   313.6      .1       0
Bank Sta=298.6,313.6
XS Rating Curve= 0 ,0
Exp/Cntr=0.3,0.1

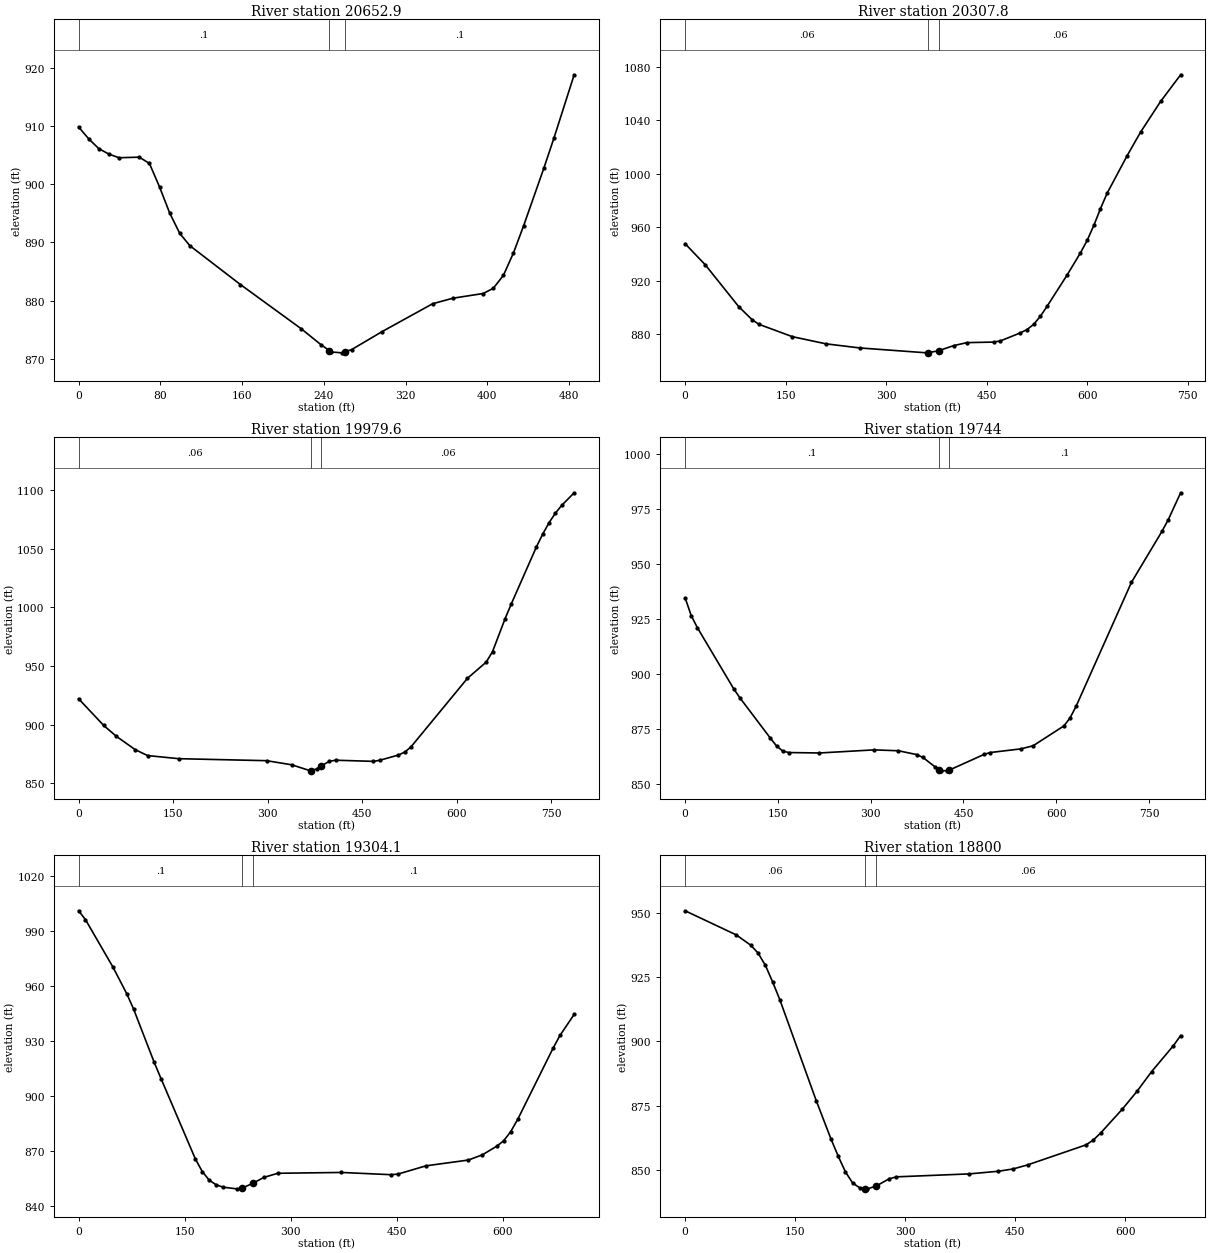
Type RM Length L Ch R = 1 ,20652.9 ,340,345.3,350.9
XS GIS Cut Line= 2
      1873492.06      398610.996     1873875.891      398314.292
#Sta/Elev= 30
       0  909.81     9.9  907.78    19.8   906.1    29.7  905.16    39.6  904.54
    59.4  904.64    69.3  903.56    79.2  899.53    89.1  895.06      99  891.54
   108.9  889.43   158.4  882.76   217.8  875.18   237.6  872.38   245.5  871.42
   247.5  871.18   257.4  871.03   260.5  871.21   267.3  871.59     297  874.67
   346.5  879.46   366.3  880.41     396  881.22   405.9  882.11   415.8  884.33
   425.7   888.2   435.6  892.85   455.4  902.74   465.3  907.92   485.1  918.79
#Mann= 3 , 0 , 0
       0      .1       0   245.5    .045       0   260.5      .1       0
Bank Sta=245.5,260.5
XS Rating Curve= 0 ,0
Exp/Cntr=0.3,0.1

Type RM Length L Ch R = 1 ,20307.8 ,328.8,328.1,327.2
XS GIS Cut Line= 3
     1873565.059      398893.571     1873897.238      398729.275
      1874229.11       398568.61
#Sta/Elev= 30
       0  947.58      30  931.84    80.1   900.4   100.2   890.6   110.2  887.23
   160.2  877.97   210.3  872.62   260.4  869.56   360.6  865.89   363.1     866
   378.1  867.45   400.5  871.27   420.4  873.53   460.3  873.94   470.2  874.79
   500.1   880.8   510.1  883.33   520.1  887.23     530  893.21     540  900.68
   569.9  924.12   589.8  940.67   599.8  949.99   609.8  961.25   619.7  973.81
   629.7  985.41   659.6 1013.54   679.5 1031.05   709.4 1054.03   739.3 1073.99
#Mann= 3 , 0 , 0
       0     .06       0   363.1    .045       0   378.1     .06       0
Bank Sta=363.1,378.1
XS Rating Curve= 0 ,0
Exp/Cntr=0.3,0.1

Type RM Length L Ch R = 1 ,19979.6 ,233.7,235.6,237.6
XS GIS Cut Line= 3
     1873661.605      399060.761      1873939.47       399074.89
     1874387.874      398836.225
#Sta/Elev= 30
       0  922.08    39.8  899.38    59.6  890.26    89.4  878.93   109.3  873.77
     159  871.12   298.1  869.41     338  865.93   367.9  860.77   368.9  860.94
   377.8  862.42   383.9  864.65   397.7  868.86   407.7  869.81   467.5  868.84
   477.4   869.7   507.3  874.22   517.3  876.68   527.2  881.11   616.9  939.53
   646.8  953.39   656.7  962.27   676.6  990.29   686.6 1003.06   726.4 1051.51
   736.4 1062.38   746.4 1072.01   756.3 1080.02   766.3 1086.64   786.2 1097.44
#Mann= 3 , 0 , 0
       0     .06       0   368.9    .045       0   383.9     .06       0
Bank Sta=368.9,383.9
XS Rating Curve= 0 ,0
Exp/Cntr=0.3,0.1

Type RM Length L Ch R = 1 ,19744   ,444.9,439.8,434.7
XS GIS Cut Line= 3
     1873736.432      399407.422     1874153.756      399230.306
     1874419.848      399006.601
#Sta/Elev= 30
       0  934.84     9.9  926.73    19.7  921.31    78.8  893.34    88.7   889.3
     138  870.94   147.8  867.47   157.7  865.16   167.5  864.46   216.8  864.26
   305.5  865.67   344.9  865.27   374.5  863.52   384.4  862.23   404.1  857.92
   411.2  856.73   413.9  856.28   423.8  856.14   426.2  856.37   483.2   863.6
   493.1  864.46   542.8  866.13   562.6  867.55   612.3  876.57   622.2  880.16
   632.1  885.55   721.5  941.87   771.2  965.23   781.1  970.41     801  982.59
#Mann= 3 , 0 , 0
       0      .1       0   411.2    .045       0   426.2      .1       0
Bank Sta=411.2,426.2
XS Rating Curve= 0 ,0
Exp/Cntr=0.3,0.1

Type RM Length L Ch R = 1 ,19304.1 ,509.1,504.1,499.1
XS GIS Cut Line= 3
     1874101.951      399786.822     1874330.366      399621.986
     1874657.682      399360.604
#Sta/Elev= 30
       0 1001.16     9.7   996.3    48.6  970.32      68  955.84    77.7  947.43
   106.8  918.32   116.6   909.3   165.1   865.4   174.8  858.59   184.6  853.87
   194.3  851.36     204  850.05   223.4  849.12   231.5  849.55   246.5   852.2
   262.2  855.42   281.7  857.63   371.4  858.08   441.2  856.86   451.2  857.16
   491.1   861.7     551  864.86   570.9  867.74   590.8  872.34   600.8  875.35
   610.8  880.34   620.8  887.14   670.6  925.89   680.6  933.04   700.6  944.51
#Mann= 3 , 0 , 0
       0      .1       0   231.5    .045       0   246.5      .1       0
Bank Sta=231.5,246.5
XS Rating Curve= 0 ,0
Exp/Cntr=0.3,0.1

Type RM Length L Ch R = 1 ,18800   ,484.8,481.6,478.3
XS GIS Cut Line= 2
      1874445.75      400224.813     1874893.161      399718.533
#Sta/Elev= 30
       0  950.87    69.6   941.5    89.4   937.5    99.4  934.43   109.3  929.72
   119.2  923.28   129.2  916.21   178.8  876.94   198.7  862.16   208.6  855.42
   218.6   849.2   228.5  844.86   238.5  842.93   245.2  842.71   248.4  842.61
   260.2  843.65   278.2  846.52   288.1  847.28   387.5  848.43   427.2  849.46
   447.1  850.35     467  851.93   546.5  859.72   556.4  861.59   566.4   864.3
   596.2  873.67     616  880.54   635.9   888.2   665.7  898.34   675.6  902.29
#Mann= 3 , 0 , 0
       0     .06       0   245.2    .045       0   260.2     .06       0
Bank Sta=245.2,260.2
XS Rating Curve= 0 ,0
Exp/Cntr=0.3,0.1

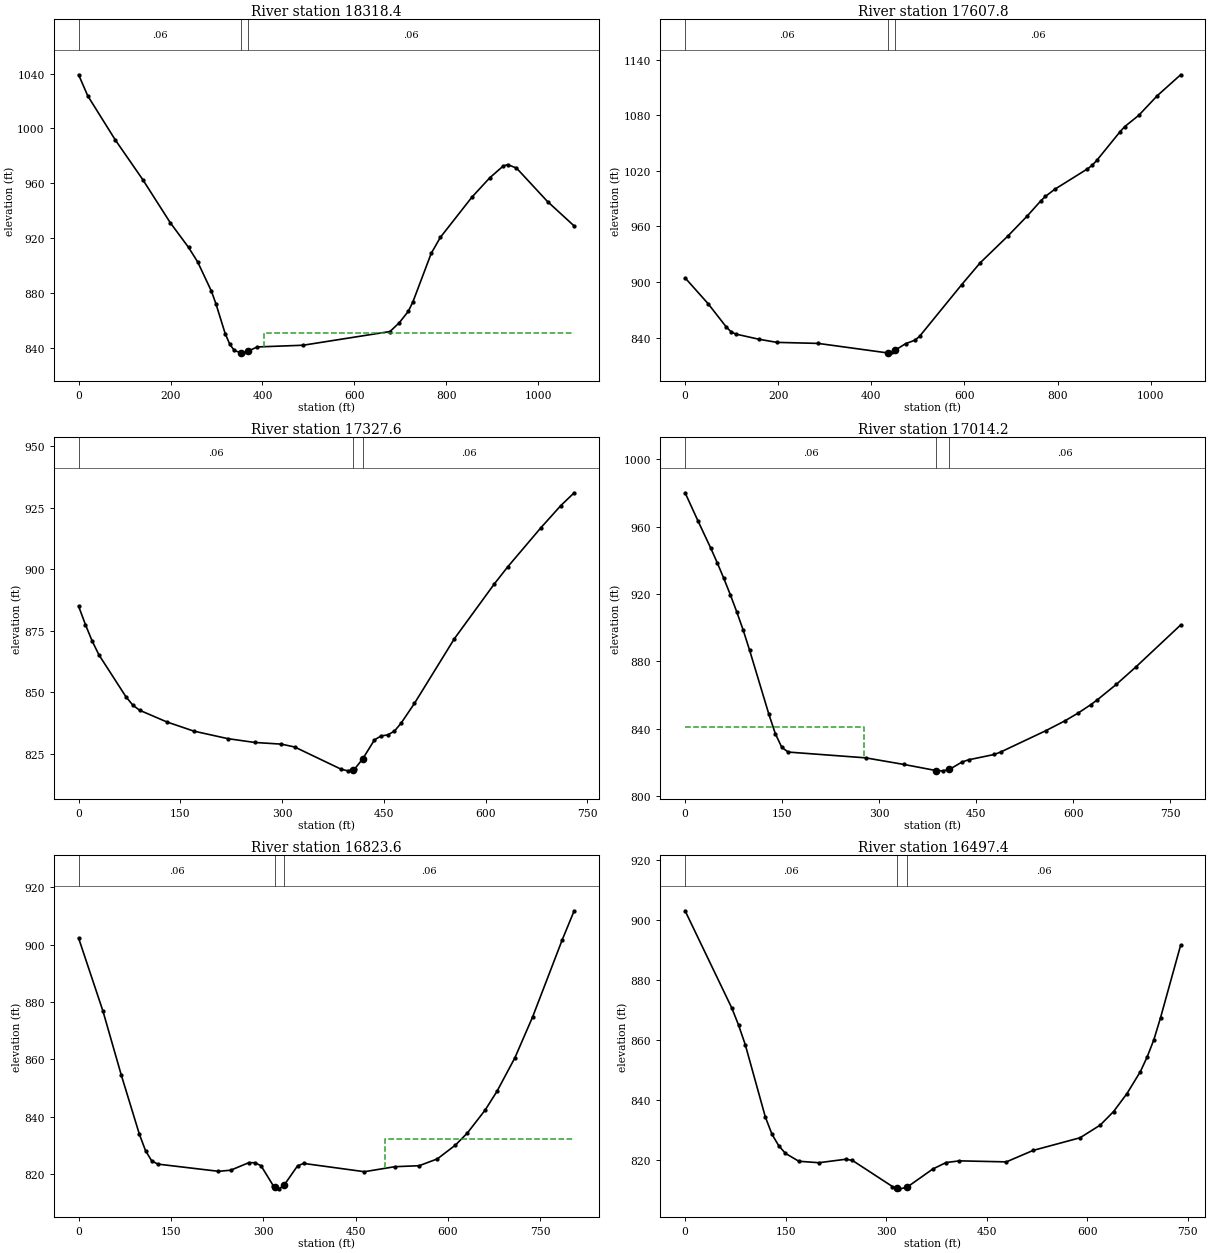
Type RM Length L Ch R = 1 ,18318.4 ,687.9,710.7,733
XS GIS Cut Line= 3
     1874813.098      400603.934      1875267.01      399912.802
     1875437.118      399727.952
#Sta/Elev= 30
       0 1039.13    19.9 1023.71    79.7   991.6   139.5  962.62   199.2  931.22
   239.1  913.13     259  902.49   288.9  881.15   298.9  871.74   318.8  850.22
   328.8  842.42   338.7  837.86   352.8  836.18   358.6  836.14   367.8  837.22
   388.5  840.44   488.2  841.69   677.4   851.7   697.4  858.03   717.3  866.48
   727.2  873.31   767.1  908.77     787  920.45   855.8  949.86   894.5  963.94
   923.5  972.46   933.1  973.57   952.5  971.07  1020.1   946.6  1078.1  928.76
#Mann= 3 , 0 , 0
       0     .06       0   352.8    .045       0   367.8     .06       0
#XS Ineff= 2 , 0
                           403.9           850.6
Permanent Ineff=
       F       F
Bank Sta=352.8,367.8
XS Rating Curve= 0 ,0
Exp/Cntr=0.3,0.1

Type RM Length L Ch R = 1 ,17607.8 ,274.8,280.1,285.8
XS GIS Cut Line= 3
     1875090.963      400726.383     1875534.481      400731.897
     1876155.329      400728.738
#Sta/Elev= 30
       0  904.48    49.3  876.69    88.7  851.35    98.6   846.4   108.4   843.9
   157.7  838.33   197.1  834.87   285.8  833.76   433.7  823.58   436.1  823.79
   443.6  824.43   451.1   826.4   473.6  833.46   493.6   837.2   503.6  841.36
   593.8  896.98   633.8   920.7   693.9  949.92     734  970.78     764  987.55
     774   992.4     794 1000.06   864.1 1022.04   874.2 1025.88   884.2  1031.2
   934.2 1062.15   944.2 1067.66   974.3  1079.8  1014.3  1101.1  1064.4 1123.63
#Mann= 3 , 0 , 0
       0     .06       0   436.1    .045       0   451.1     .06       0
Bank Sta=436.1,451.1
XS Rating Curve= 0 ,0
Exp/Cntr=0.3,0.1

Type RM Length L Ch R = 1 ,17327.6 ,318.1,313.4,308.6
XS GIS Cut Line= 3
     1875076.835      400957.153     1875326.442      400966.572
     1875792.691      401084.311
#Sta/Elev= 30
       0  884.99      10  877.56      20  870.85      30  865.23    69.9   848.2
    79.9  844.86    89.9  842.78   129.9  838.05   169.8  834.31   219.8  831.26
   259.6   829.7   298.9  829.02   318.5  827.87   387.2  818.82     397  818.18
     404  818.67   406.8  818.86     419  823.08   436.2  830.74   446.1  832.36
   455.9  832.77   465.7  834.32   475.5  837.53   495.1  845.53     554   871.8
   612.9  894.04   632.5  900.92   681.6  916.86     711  925.86   730.7  931.06
#Mann= 3 , 0 , 0
       0     .06       0     404    .045       0     419     .06       0
Bank Sta=404,419
XS Rating Curve= 0 ,0
Exp/Cntr=0.3,0.1

Type RM Length L Ch R = 1 ,17014.2 ,191.3,190.7,190
XS GIS Cut Line= 3
     1875021.659      401299.576     1875519.535      401317.436
     1875773.853      401232.663
#Sta/Elev= 30
       0  980.13    19.9  963.42    39.9  947.04    49.8  938.45    59.8  929.32
    69.8  919.67    79.7  909.54    89.7  898.67    99.6  886.73   129.5  848.56
   139.5  836.99   149.5  828.83   159.4  826.02     279  822.59   338.8  818.63
   388.6  814.99   398.6  814.86   408.5  815.66   428.4  820.14   438.4  821.42
   478.3   824.6   488.2  826.08   557.8  838.72   587.6  844.63   607.4  849.11
   627.3  854.16   637.2  856.98     667   866.3   696.8   876.5   766.3  901.55
#Mann= 3 , 0 , 0
       0     .06       0   388.6    .045       0   408.5     .06       0
#XS Ineff= 2 , 0
          277.22  841.11
Permanent Ineff=
       F       F
Bank Sta=388.6,408.5
XS Rating Curve= 0 ,0
Exp/Cntr=0.3,0.1

Type RM Length L Ch R = 1 ,16823.6 ,331.6,326.1,317
XS GIS Cut Line= 3
     1875083.899       401501.11     1875686.725      401505.819
     1875879.818      401444.595
#Sta/Elev= 30
       0  902.29    39.5  876.87    69.2  854.62    98.8  833.82   108.7  828.15
   118.6  824.62   128.5  823.45   227.3  820.93   247.1  821.31   276.7  823.95
   286.6  823.92   296.5  822.86   316.2  815.96   319.1  815.62   326.1  814.81
   334.1  816.14   355.8  822.83   365.7  823.68   464.5  820.79   513.9  822.54
   553.4  822.88   583.1  825.27   612.5   830.1   631.8   834.3   660.7   842.3
     680  848.87     709  860.53   737.9  874.84   786.1  901.79   805.4  911.87
#Mann= 3 , 0 , 0
       0     .06       0   319.1    .045       0   334.1     .06       0
#XS Ineff= 2 , 0
                          497.46          832.16
Permanent Ineff=
       F       F
Bank Sta=319.1,334.1
XS Rating Curve= 0 ,0
Exp/Cntr=0.3,0.1

Type RM Length L Ch R = 1 ,16497.4 ,240.8,232,226.8
XS GIS Cut Line= 3
       1875182.8       401884.94     1875493.633      401811.942
     1875879.818      401647.107
#Sta/Elev= 30
       0  903.11    69.8  870.58    79.8  864.93    89.8  858.38   119.7  834.27
   129.7  828.46   139.7  824.68   149.7  822.13   169.6   819.5   199.6  819.01
   239.5  820.16   249.4   819.8   309.3  811.06   315.5  810.58   319.3  810.29
   330.5  810.74   369.3  816.88   389.3  819.07   409.3  819.63   479.2  819.29
   519.2  823.12   589.2  827.34   619.2  831.56   639.2   836.1   659.2  842.11
   679.2  849.45   689.2  854.28   699.2  860.03   709.2  867.41   739.2  891.62
#Mann= 3 , 0 , 0
       0     .06       0   315.5    .045       0   330.5     .06       0
Bank Sta=315.5,330.5
XS Rating Curve= 0 ,0
Exp/Cntr=0.3,0.1

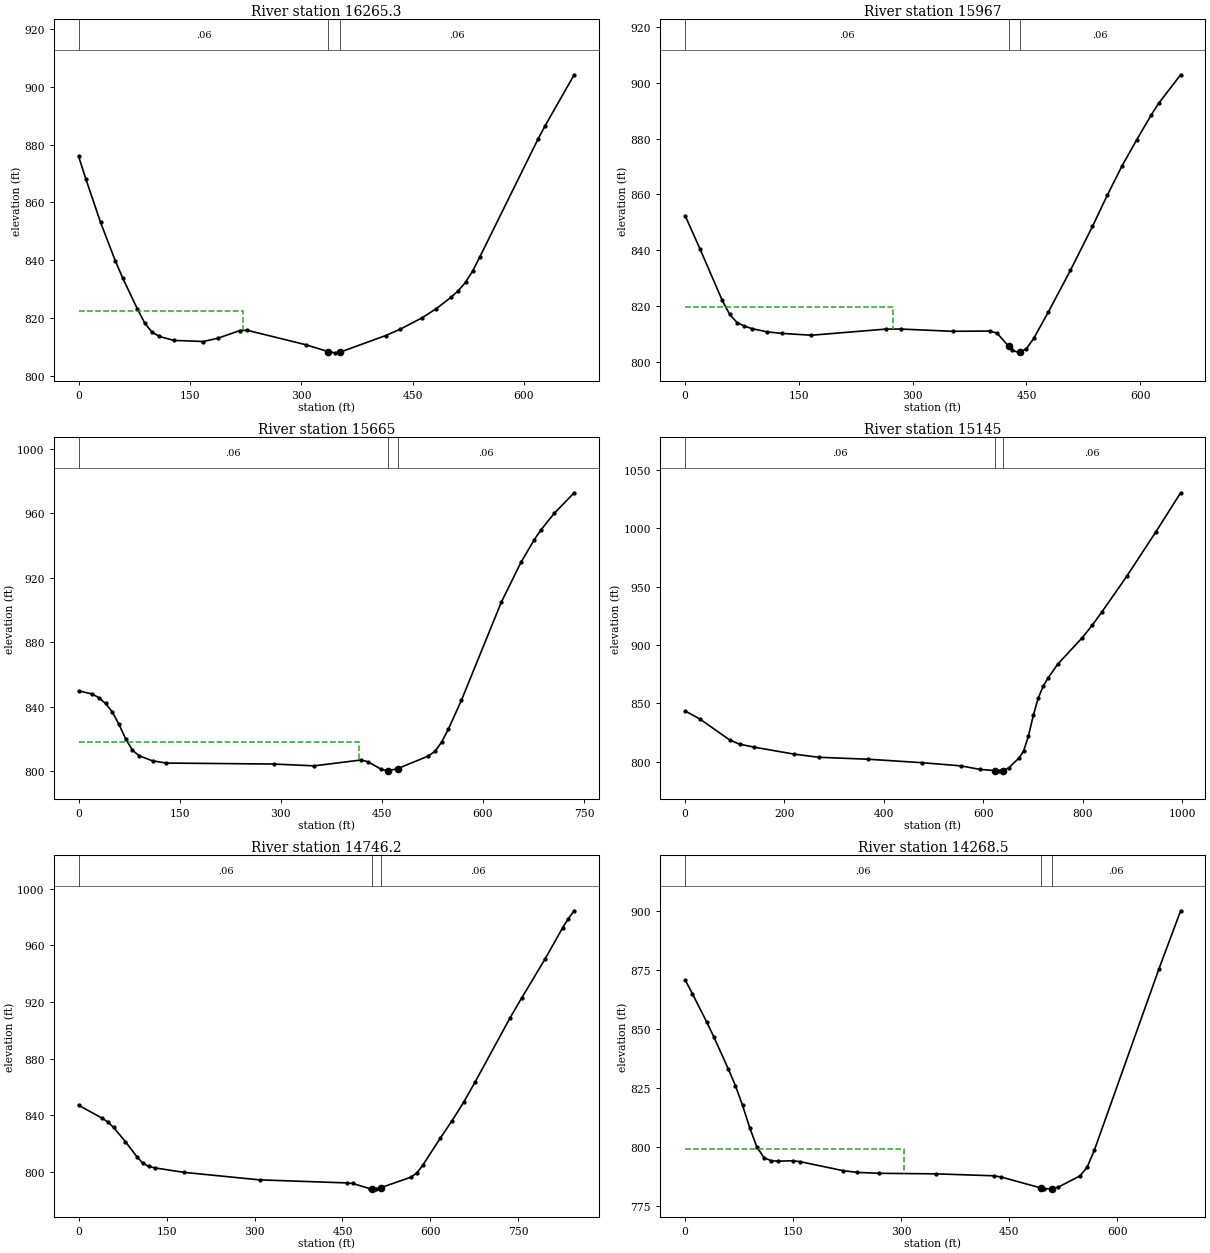
Type RM Length L Ch R = 1 ,16265.3 ,291,298.4,305.7
XS GIS Cut Line= 4
     1875307.604      402113.355     1875599.598      402021.518
     1875726.222      401929.521     1875924.559      401877.876
#Sta/Elev= 30
       0  875.92     9.9  867.97    29.6  853.07    49.4  839.83    59.2  833.96
      79  823.25    88.9  818.37    98.7  815.19   108.6  813.67   128.4   812.3
   167.9  811.92   187.6  813.06   217.2   815.7   227.1   815.8   306.1   810.8
   336.6  808.39   345.2     808   351.6  808.18   413.7  813.98   433.3  816.19
   462.6   820.1   482.1  823.31   501.6  827.19   511.4  829.47   521.2  832.38
   530.9  836.33   540.7  841.27   618.8  881.86   628.5  886.54   667.6  904.15
#Mann= 3 , 0 , 0
       0     .06       0   336.6    .045       0   351.6     .06       0
#XS Ineff= 2 , 0
          221.97  822.36
Permanent Ineff=
       F       F
Bank Sta=336.6,351.6
XS Rating Curve= 0 ,0
Exp/Cntr=0.3,0.1

Type RM Length L Ch R = 1 ,15967   ,300.2,302.1,304
XS GIS Cut Line= 3
     1875366.474      402322.932     1875762.079      402254.643
     1876002.267      402179.289
#Sta/Elev= 30
       0  852.43    19.6  840.46      49  821.95    58.8  816.92    68.5     814
    78.3  812.71    88.1  811.85   107.7  810.69   127.3  810.12   166.5  809.46
   264.4  811.66     284  811.69   352.5  810.87   401.5  810.96   411.1  810.23
   426.5  805.48   430.5  804.21   440.2  803.14   441.5  803.34   449.9  804.65
   459.6  808.36   478.9  817.83     508   832.8     537  848.52   556.4  859.66
   575.7  870.11   595.1  879.53   614.5  888.55   624.1  892.67   653.2  902.96
#Mann= 3 , 0 , 0
       0     .06       0   426.5    .045       0   441.5     .06       0
#XS Ineff= 2 , 0
          274.05  819.46
Permanent Ineff=
       F       F
Bank Sta=426.5,441.5
XS Rating Curve= 0 ,0
Exp/Cntr=0.3,0.1

Type RM Length L Ch R = 1 ,15665   ,522.7,519.9,517.2
XS GIS Cut Line= 3
     1875422.989      402636.119      1875919.85      402525.444
     1876112.943      402407.704
#Sta/Elev= 30
       0  849.82      20  847.92    29.9   845.6    39.9  842.04    49.9  836.83
    59.9     829    69.9  819.96    79.8  813.06    89.8  809.57   109.8  806.44
   129.8  805.08   289.4  804.47   349.3  803.34   419.2  806.98   429.2  805.88
   449.2  801.16   458.5  800.31   459.1  800.25   473.5  801.65   518.9  809.45
   528.7  812.36   538.5  818.04   548.4  825.98     568  844.07     627  904.74
   656.5  929.76   676.2  943.68     686   949.7   705.7  959.98   735.2  972.68
#Mann= 3 , 0 , 0
       0     .06       0   458.5    .045       0   473.5     .06       0
#XS Ineff= 2 , 0
          415.23  818.34
Permanent Ineff=
       F       F
Bank Sta=458.5,473.5
XS Rating Curve= 0 ,0
Exp/Cntr=0.3,0.1

Type RM Length L Ch R = 1 ,15145   ,398.3,398.8,399.4
XS GIS Cut Line= 4
     1875731.466      403392.007     1875990.168      403026.101
     1876218.908      402944.596     1876513.257      402859.824
#Sta/Elev= 30
       0  843.48    29.9  836.54    89.6  818.66   109.5  815.02   139.4  812.43
   219.1  806.51   268.9  803.79   368.5  802.14   477.3  799.15     555  796.45
   593.8  793.38   623.8  792.44   632.7  792.19   638.8  792.45   642.4   792.6
   652.1     795   671.5  802.97   681.2  808.99     691  822.02   700.8  839.66
   710.7  854.52   720.6   864.5   730.5  871.71   750.2  883.65   799.6  906.29
   819.4  916.87   839.2  928.45   888.6   958.6   947.9  997.07   997.3 1030.25
#Mann= 3 , 0 , 0
       0     .06       0   623.8    .045       0   638.8     .06       0
Bank Sta=623.8,638.8
XS Rating Curve= 0 ,0
Exp/Cntr=0.3,0.1

Type RM Length L Ch R = 1 ,14746.2 ,476.4,477.7,479
XS GIS Cut Line= 3
     1875846.851      403488.553     1876393.163      403302.525
     1876609.804      403144.754
#Sta/Elev= 30
       0  847.03    39.8  838.03    49.8  835.28    59.7  831.38    79.6  821.49
    99.5   810.7   109.4  806.21   119.4  803.86   129.4  802.91   179.1  799.74
   308.5  794.42   457.7  792.26   467.7  791.85   497.5  788.08   501.1  788.09
   507.5  788.11   516.1     789   567.2  796.41   577.1  799.41     587  804.85
   616.8  823.89   636.7  836.09   656.5   849.1   676.4  863.64   735.9  908.88
   755.8  922.97   795.5  950.35   825.3  972.26   835.2  978.85   845.1  984.35
#Mann= 3 , 0 , 0
       0     .06       0   501.1    .045       0   516.1     .06       0
Bank Sta=501.1,516.1
XS Rating Curve= 0 ,0
Exp/Cntr=0.3,0.1

Type RM Length L Ch R = 1 ,14268.5 ,397.1,397.8,398.6
XS GIS Cut Line= 3
     1875983.429      403891.222     1876522.676       403747.58
      1876652.19      403738.161
#Sta/Elev= 30
       0  870.92      10  865.14    29.9  853.15    39.9  846.78    59.8  833.33
    69.8  826.18    79.7  817.82    89.7  808.37    99.6  800.17   109.6  795.65
   119.6  794.34   129.6  794.17   149.5  794.34   159.4  793.98   219.2  790.16
   239.2  789.42   269.1  789.04   348.8   788.8   428.5  787.98   438.5  787.48
   493.9  782.83   498.3  782.54   508.2  782.46   508.9  782.51   518.2  783.22
   548.1  787.92     558  791.54     568  798.72   657.9  875.66   687.9  900.16
#Mann= 3 , 0 , 0
       0     .06       0   493.9    .045       0   508.9     .06       0
#XS Ineff= 2 , 0
          303.23  799.19
Permanent Ineff=
       F       F
Bank Sta=493.9,508.9
XS Rating Curve= 0 ,0
Exp/Cntr=0.3,0.1