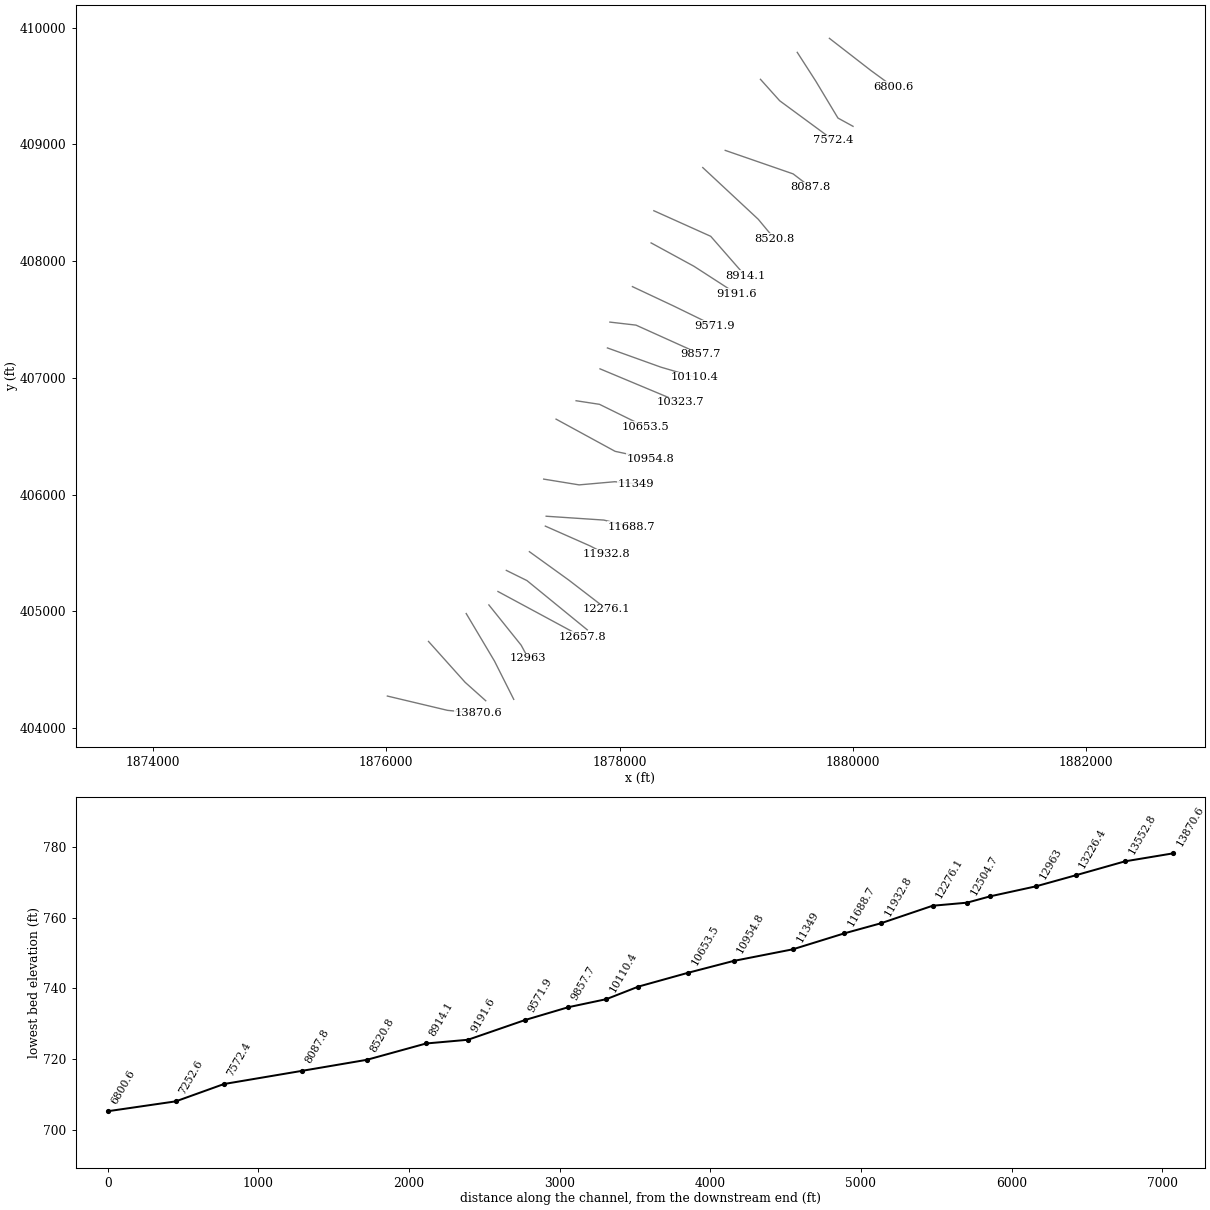
HEC-RAS study ArmstrngCk.prj: ArmstrngCk

--- ArmstrngCk.g01 (geometry) --- (continued)

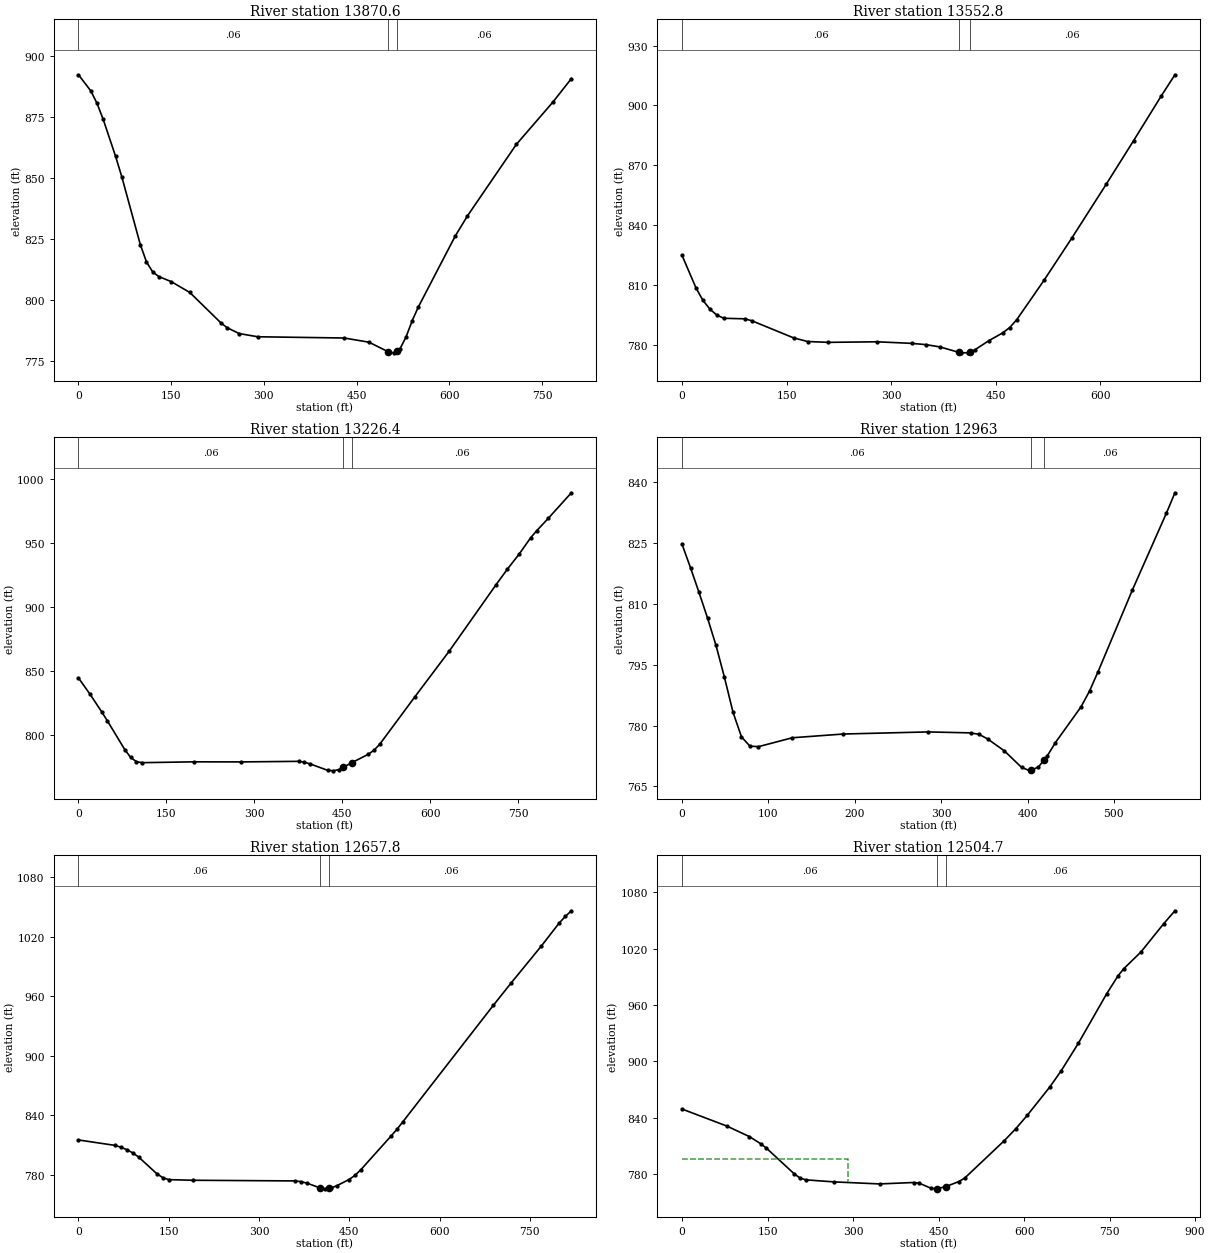
Type RM Length L Ch R = 1 ,13870.6 ,331.5,317.8,304
XS GIS Cut Line= 3
     1876009.332      404275.053     1876525.031      404152.604
     1876791.122      404126.702
#Sta/Elev= 30
       0  892.18      20  885.54      30  880.43      40  873.86      60  858.75
      70   850.4     100  822.56     110  815.44     120  811.37     130  809.43
     150  807.38     180  802.93     230  790.56     240  788.54     260  786.07
     290  784.76     430  784.25     470  782.53   500.4  778.69     510  778.17
   515.4  779.03     520  779.77     530  784.71   539.9  791.37   549.8  796.97
   609.2  825.92   629.1  834.25   708.3  863.62   767.7  881.04   797.4  890.62
#Mann= 3 , 0 , 0
       0     .06       0   500.4    .045       0   515.4     .06       0
Bank Sta=500.4,515.4
XS Rating Curve= 0 ,0
Exp/Cntr=0.3,0.1

Type RM Length L Ch R = 1 ,13552.8 ,330.8,326.4,321.6
XS GIS Cut Line= 3
     1876361.933      404742.757     1876675.738      404392.793
     1876852.347      404235.022
#Sta/Elev= 30
       0  824.79      20  808.49      30   802.2      40  797.84      50  794.83
      60  793.25      90  792.98     100  792.02     160  783.42     180   781.6
     210  781.18     280  781.46     330  780.66     350  780.02     370  778.88
   397.6  776.11     400  775.92     410  775.99   412.6  776.37     420  777.44
     440  782.01     460  785.95     470  788.62   479.9  792.48   519.4  812.42
   558.9  833.41   608.2  860.38   647.7  882.36   687.1  904.64   706.9  915.36
#Mann= 3 , 0 , 0
       0     .06       0   397.6    .045       0   412.6     .06       0
Bank Sta=397.6,412.6
XS Rating Curve= 0 ,0
Exp/Cntr=0.3,0.1

Type RM Length L Ch R = 1 ,13226.4 ,260.3,263.4,267.1
XS GIS Cut Line= 3
     1876685.157      404981.491       1876927.7      404574.112
     1877092.536      404246.796
#Sta/Elev= 30
       0  844.63    19.8  831.82    39.5  818.18    49.4  810.98      79  788.53
    88.9   782.5    98.8  779.12   108.6  778.37   197.6  779.03   276.6  778.96
   375.3  779.41   385.2  778.72   395.1  777.38   424.7  772.43   434.6  771.98
   444.5  773.02   451.2  774.68   466.2  778.37   493.9  784.85   503.8  788.04
   513.7  792.74   573.2  829.59   632.6  865.82   711.8  917.37   731.6  929.85
   751.4  941.44   771.3   954.4   781.2  959.66     801   969.4   840.6  989.49
#Mann= 3 , 0 , 0
       0     .06       0   451.2    .045       0   466.2     .06       0
Bank Sta=451.2,466.2
XS Rating Curve= 0 ,0
Exp/Cntr=0.3,0.1

Type RM Length L Ch R = 1 ,12963   ,296.2,305.2,314.2
XS GIS Cut Line= 3
     1876879.343      405055.421     1877156.115       404710.69
      1877217.34       404597.66
#Sta/Elev= 30
       0  824.74     9.8  818.96    19.6  812.89    29.5  806.55    39.3  799.82
    49.1  791.92      59  783.32    68.8  777.24    78.6  774.95    88.4  774.82
   127.7  777.02   186.7  777.94   284.9  778.46     334  778.22   343.8  777.86
   353.7  776.74   373.3  773.76     393  769.72   402.8  768.86   404.4  769.02
   412.6  769.82   419.4  771.61   422.4   772.4   432.3  775.84   461.9  784.64
   471.8  788.56   481.6   793.3   521.2  813.39   560.8  832.44   570.6  837.44
#Mann= 3 , 0 , 0
       0     .06       0   404.4    .045       0   419.4     .06       0
Bank Sta=404.4,419.4
XS Rating Curve= 0 ,0
Exp/Cntr=0.3,0.1

Type RM Length L Ch R = 1 ,12657.8 ,157.3,153,148.8
XS GIS Cut Line= 3
     1876957.279      405170.368     1877317.832      404976.224
     1877678.239      404781.808
#Sta/Elev= 30
       0  815.23    59.9  809.82    69.9  808.07    79.9  805.54    89.9  802.29
    99.9  798.04   129.8  781.41   139.8  777.36   149.8  775.28   189.8  774.66
   359.6  773.99   369.6  773.29   379.5  771.77     402  766.82   409.5  766.02
     417  766.59   419.5  766.78   429.5  769.24   449.4  775.34   459.4  779.54
   469.4  785.44   519.4   819.2   529.4  826.16   539.3  833.78   689.2  950.69
   719.1  973.43   769.1 1010.47     799 1033.81     809 1040.26     819 1045.95
#Mann= 3 , 0 , 0
       0     .06       0     402    .045       0     417     .06       0
Bank Sta=402,417
XS Rating Curve= 0 ,0
Exp/Cntr=0.3,0.1

Type RM Length L Ch R = 1 ,12504.7 ,227.2,228.6,229.9
XS GIS Cut Line= 3
     1877028.956      405351.193     1877205.566      405264.066
     1877722.894      404842.018
#Sta/Elev= 30
       0   849.2    78.8  831.03   118.2  819.84   137.8  812.34   147.7  807.74
   196.9  780.13   206.9  775.78   216.9  773.81   266.7  771.63   346.4  769.46
   406.2  770.97   416.2  770.21   436.1  765.01     446  764.23   447.6  764.38
   462.6  766.62   485.9  772.04   495.9   775.7   565.6   815.7   585.6  828.36
   605.5  842.45   645.4   872.9   665.3  890.13   695.2  919.22     745  972.08
   764.9  991.12   774.9  998.66   804.8 1016.31   844.6 1046.35   864.6 1060.33
#Mann= 3 , 0 , 0
       0     .06       0   447.6    .045       0   462.6     .06       0
#XS Ineff= 2 , 0
          290.32  796.13
Permanent Ineff=
       F       F
Bank Sta=447.6,462.6
XS Rating Curve= 0 ,0
Exp/Cntr=0.3,0.1

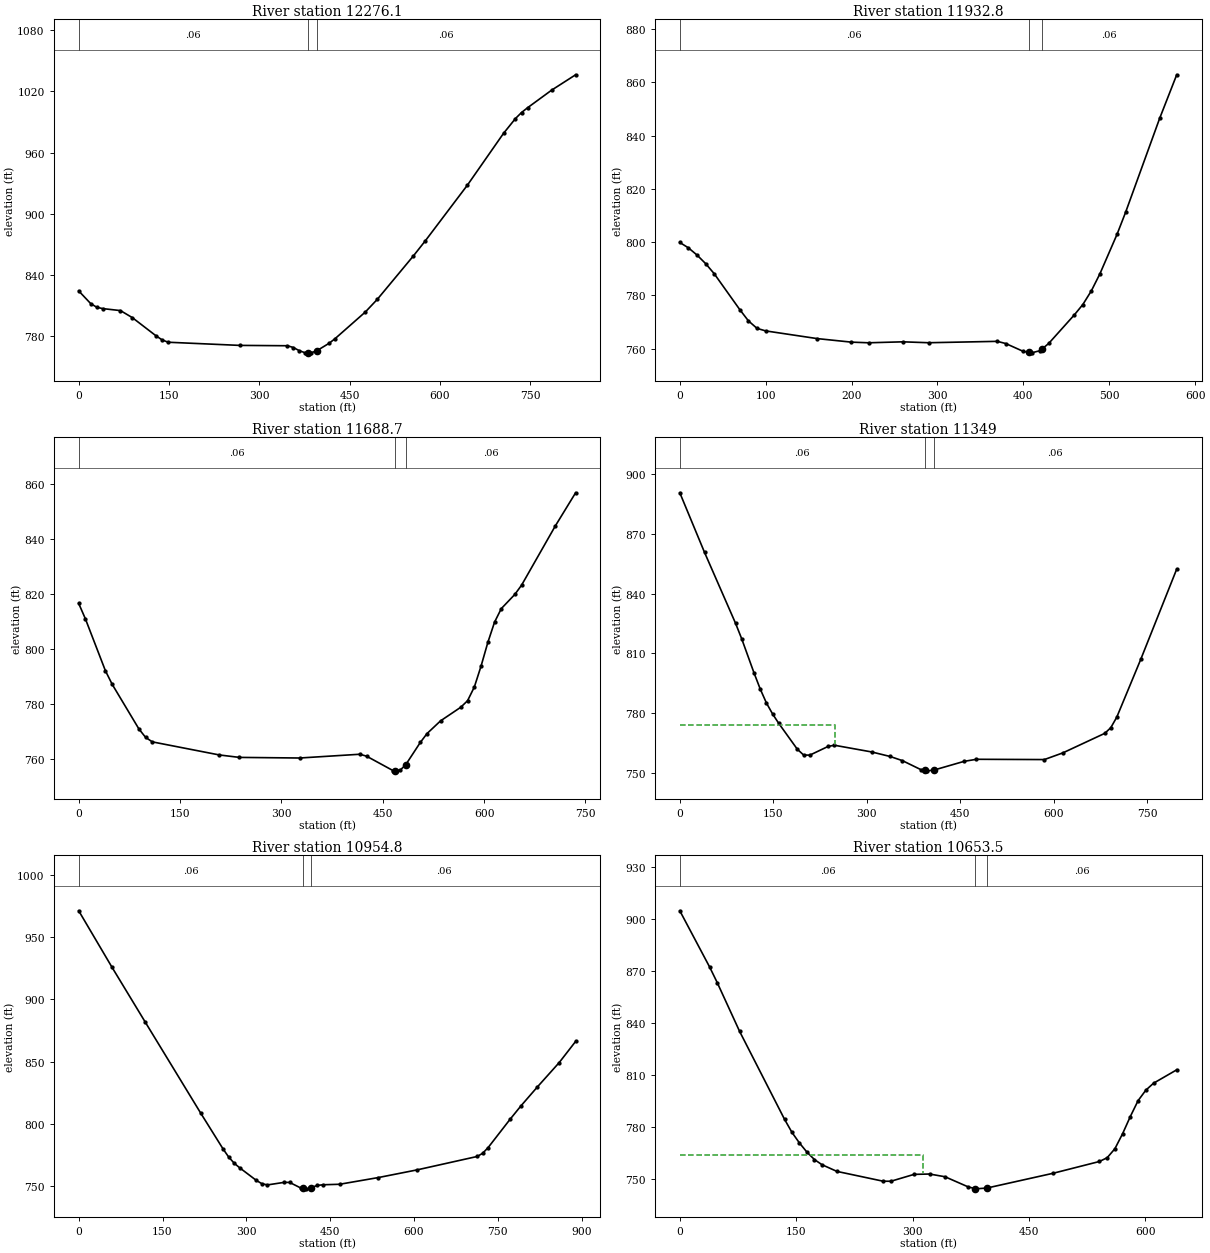
Type RM Length L Ch R = 1 ,12276.1 ,338.6,343.3,347
XS GIS Cut Line= 3
     1877226.759      405511.319     1877564.504      405268.074
     1877889.258      405018.625
#Sta/Elev= 30
       0  824.18    19.8  811.79    29.7  808.22    39.6  806.82    69.4  804.84
    89.2   797.9   128.8  779.93   138.7  776.05   148.6  773.77   267.6  770.67
   346.8  770.33   356.8  768.57   366.7  765.43   376.6  763.36   380.6  763.41
   386.5  763.48   395.6  765.39   416.2  772.78   426.2  777.39   476.2  803.41
   496.1  815.84     556  858.43     576  873.38   645.9  928.02   705.9  978.86
   725.8  993.45   735.8  999.31   745.8 1003.98   785.8 1021.27   825.7 1036.38
#Mann= 3 , 0 , 0
       0     .06       0   380.6    .045       0   395.6     .06       0
Bank Sta=380.6,395.6
XS Rating Curve= 0 ,0
Exp/Cntr=0.3,0.1

Type RM Length L Ch R = 1 ,11932.8 ,236.2,244.2,252.5
XS GIS Cut Line= 3
     1877363.337      405730.314     1877747.168      405560.769
     1877888.455      405487.771
#Sta/Elev= 30
       0  799.88      10  797.86      20  795.17      30  791.96      40  788.17
    69.9  774.62    79.9  770.42    89.9   767.6    99.9  766.65   159.8  763.76
   199.8  762.42   219.8  762.18   259.8  762.54   289.7   762.2   369.7  762.72
   379.6  761.89   399.6  758.99   406.5  758.58   409.6   758.4   419.6  759.23
   421.5  759.75   429.6  761.95   459.4  772.67   469.3  776.56   479.2   781.7
   489.2  788.12   509.1  802.93     519  811.15   558.8  846.58   578.6   862.9
#Mann= 3 , 0 , 0
       0     .06       0   406.5    .045       0   421.5     .06       0
Bank Sta=406.5,421.5
XS Rating Curve= 0 ,0
Exp/Cntr=0.3,0.1

Type RM Length L Ch R = 1 ,11688.7 ,338,339.8,342.2
XS GIS Cut Line= 3
     1877370.401      405815.087     1877864.907       405782.12
     1878098.031      405725.605
#Sta/Elev= 30
       0  816.44     9.9  810.85    39.6  791.92    49.6     787    89.2  770.74
    99.1  767.69     109  766.07   208.2  761.31   237.9  760.42   327.1   760.2
   416.3  761.57   426.2  760.85   465.9  755.53   468.9  755.61   475.8  755.78
   483.9   757.7   505.6  765.85   515.6   769.1   535.6  773.72   565.6  778.69
   575.6  781.07   585.6  786.04   595.6   793.7   605.6  802.28   615.5  809.64
   625.5  814.57   645.5  819.73   655.5   823.1   705.5  844.68   735.5  856.73
#Mann= 3 , 0 , 0
       0     .06       0   468.9    .045       0   483.9     .06       0
Bank Sta=468.9,483.9
XS Rating Curve= 0 ,0
Exp/Cntr=0.3,0.1

Type RM Length L Ch R = 1 ,11349   ,405.6,394,382.3
XS GIS Cut Line= 4
     1877349.208      406132.984     1877652.976      406083.533
     1877958.579      406110.592     1878140.418      406092.952
#Sta/Elev= 30
       0  890.71    39.7  860.74    89.4  825.19    99.3  817.38   119.1  800.22
   129.1   792.1     139  785.11   148.9   779.6   158.8  774.87   188.6  761.88
   198.6  759.01   208.5  758.91   238.3  763.35   248.2  763.89   307.8  760.53
   337.5  758.25   357.2  756.16   386.9  751.63   392.7  751.28   396.8  751.04
   407.7  751.42   456.2  755.81     476  756.84   584.9   756.7   614.6  760.06
   681.9  769.88   691.5  772.71   701.1  777.98   739.6  807.04   797.3  852.37
#Mann= 3 , 0 , 0
       0     .06       0   392.7    .045       0   407.7     .06       0
#XS Ineff= 2 , 0
          248.72  773.89
Permanent Ineff=
       F       F
Bank Sta=392.7,407.7
XS Rating Curve= 0 ,0
Exp/Cntr=0.3,0.1

Type RM Length L Ch R = 1 ,10954.8 ,300.1,301.3,303
XS GIS Cut Line= 3
     1877455.431      406646.519     1877961.454      406370.817
     1878267.576      406304.883
#Sta/Elev= 30
       0  971.12    59.6  925.75   119.2  881.62   218.6   808.4   258.3  779.85
   268.3  773.39   278.2  768.38   288.1  764.65   317.9  754.53   327.9  751.85
   337.8  750.89   367.6  752.93   377.6  752.89   397.4  748.43   401.4  748.15
   407.4  747.74   416.4  748.81   427.2  750.48   437.2  751.01     467  751.41
   536.5  756.82   605.6  762.96   713.3  773.75     723   776.3   732.8  780.88
     772  803.56   791.5  814.35   820.9  829.57     860  849.16   889.4  866.16
#Mann= 3 , 0 , 0
       0     .06       0   401.4    .045       0   416.4     .06       0
Bank Sta=401.4,416.4
XS Rating Curve= 0 ,0
Exp/Cntr=0.3,0.1

Type RM Length L Ch R = 1 ,10653.5 ,328.6,329.8,330.4
XS GIS Cut Line= 3
     1877627.073      406804.099      1877827.23      406773.487
     1878220.481      406580.394
#Sta/Elev= 30
       0  904.69    38.6  872.14    48.2  863.33    77.1  835.17     135   784.5
   144.6  776.94   154.3   770.8   163.9  765.57   173.6  761.27   183.2  758.34
   202.5  754.46   262.2  748.79   272.2  748.78     302  752.74     322  752.94
   341.9  751.37   371.8  745.52   380.9  744.49   381.7   744.4   395.9  744.86
   481.3  753.38     541  760.17     551  762.36   560.9  767.52   570.9  776.24
   580.8   786.1   590.8  795.24   600.8  801.28   610.7  805.28   640.6  813.01
#Mann= 3 , 0 , 0
       0     .06       0   380.9    .045       0   395.9     .06       0
#XS Ineff= 2 , 0
          313.73  763.89
Permanent Ineff=
       F       F
Bank Sta=380.9,395.9
XS Rating Curve= 0 ,0
Exp/Cntr=0.3,0.1

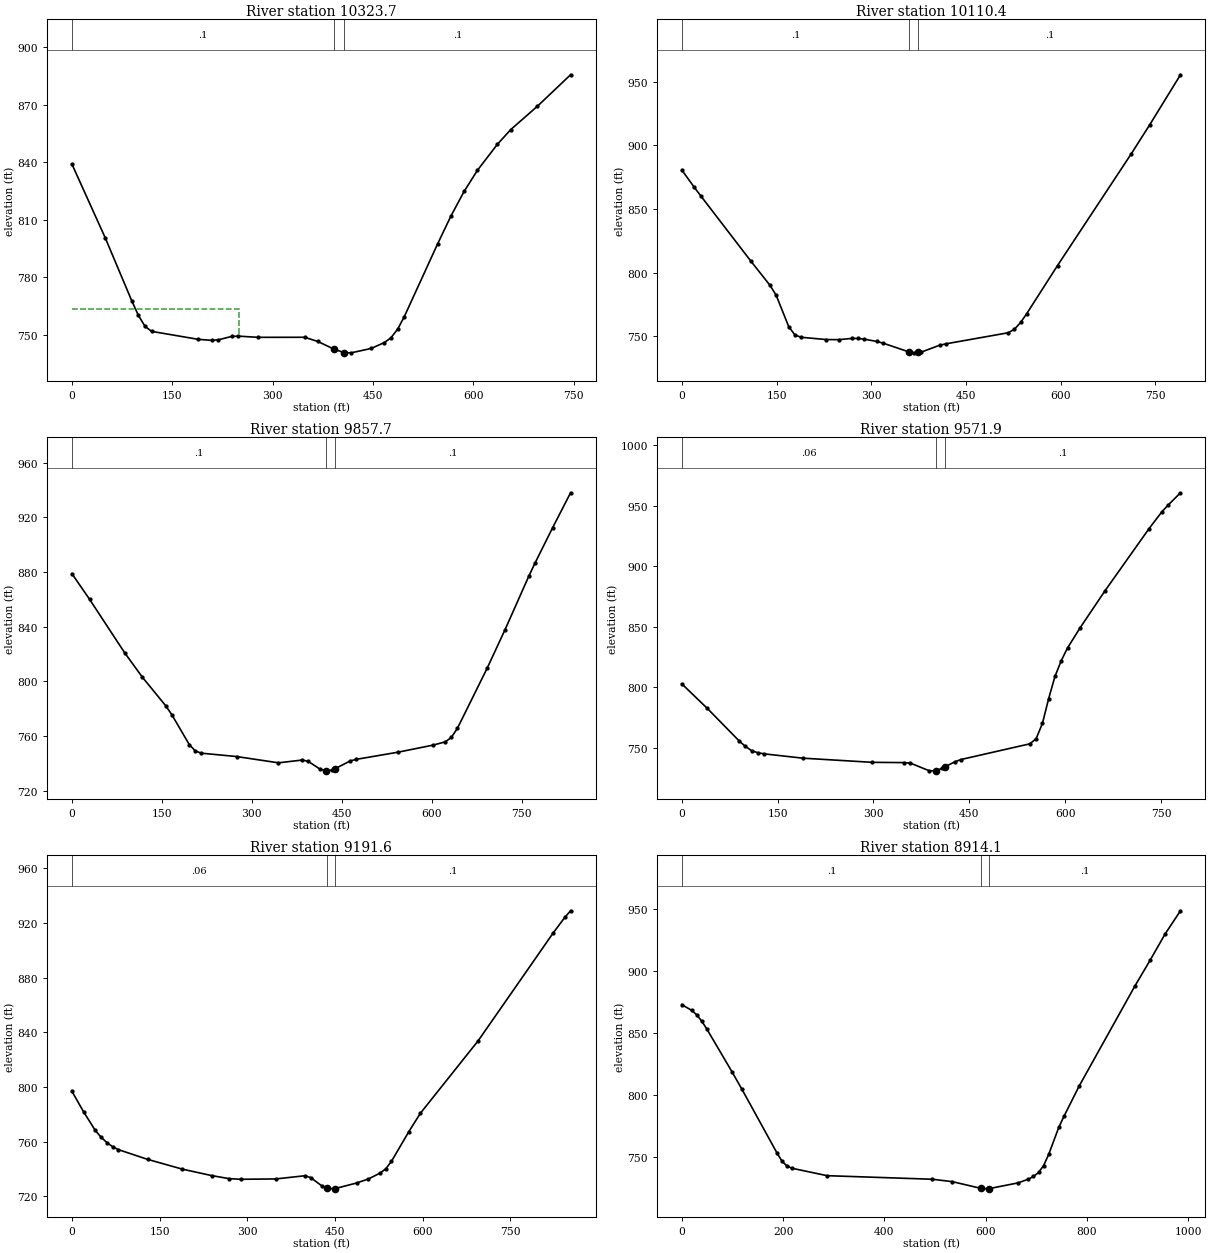
Type RM Length L Ch R = 1 ,10323.7 ,212,213.3,214.5
XS GIS Cut Line= 2
      1877831.94      407077.255     1878519.539       406789.97
#Sta/Elev= 30
       0  839.02    49.7   800.6    89.4  767.68    99.4     760   109.3  754.28
   119.2  751.69   188.8  747.54   208.7  747.02   218.6  747.27   238.5  749.04
   248.4  749.21   278.2  748.59   347.8  748.61   367.6  746.41   392.1  742.34
   407.1  740.58   417.3  740.49   447.1  742.77     467  745.87   476.9   748.4
   486.9  752.92   496.8  759.45   546.5  797.37   566.4   811.9   586.2  824.82
   606.1  835.82   635.9  849.39   655.8  857.03   695.5  869.18   745.2  885.64
#Mann= 3 , 0 , 0
       0      .1       0   392.1    .045       0   407.1      .1       0
#XS Ineff= 2 , 0
          250.13  763.38
Permanent Ineff=
       F       F
Bank Sta=392.1,407.1
XS Rating Curve= 0 ,0
Exp/Cntr=0.3,0.1

Type RM Length L Ch R = 1 ,10110.4 ,254.6,252.8,251
XS GIS Cut Line= 3
     1877895.519      407256.219     1878354.704      407091.384
     1878644.343      407006.611
#Sta/Elev= 30
       0   880.7    19.9     867    29.9  860.45   109.5  808.96   139.4  790.19
   149.4  782.24   169.3  757.53   179.2  750.94   189.2  749.16     229  747.36
   248.9   747.3   268.8  748.25   278.8  748.27   288.7  747.68   308.6  745.92
   318.6  744.57   359.6  737.67   368.4  736.93   374.6   737.2   378.4  737.36
   408.2  742.89   418.2  744.01   517.1  752.74   526.8  755.56   536.6  760.86
   546.3  767.83     595  805.61   711.8   893.5     741  916.32   789.7  955.62
#Mann= 3 , 0 , 0
       0      .1       0   359.6    .045       0   374.6      .1       0
Bank Sta=359.6,374.6
XS Rating Curve= 0 ,0
Exp/Cntr=0.3,0.1

Type RM Length L Ch R = 1 ,9857.7  ,286.3,285.7,285
XS GIS Cut Line= 3
     1877916.713      407477.569     1878140.418      407451.667
     1878693.261      407202.389
#Sta/Elev= 30
       0  878.81    29.4  860.07    88.1  820.88   117.5  803.11   156.7  782.09
   166.4  775.83   195.8   753.8   205.6  749.28   215.4  747.58   274.9  745.09
   344.5  740.51   384.3  742.56   394.2  741.55   414.1  735.79   423.8  734.65
     434  735.24   438.8   736.2   463.8  741.82   473.7  743.01   543.3  748.24
     603  753.52   622.9  755.89   632.8  759.14   642.8  765.66   692.5   809.7
   722.3  837.84     762  877.03     772  886.29   801.8  912.52   831.6  937.93
#Mann= 3 , 0 , 0
       0      .1       0   423.8    .045       0   438.8      .1       0
Bank Sta=423.8,438.8
XS Rating Curve= 0 ,0
Exp/Cntr=0.3,0.1

Type RM Length L Ch R = 1 ,9571.9  ,383.1,380.3,377.6
XS GIS Cut Line= 3
     1878109.805      407781.337     1878460.669      407616.502
     1878813.888      407444.602
#Sta/Elev= 30
       0  802.83    39.8  782.64    89.5  755.85    99.4  751.24   109.3  747.69
   119.3  745.92   129.2  745.05   188.9  741.52   298.2  738.06   347.9  737.84
   357.8  737.39   387.6  731.04   397.1  731.12   407.3  733.02   412.1   734.4
   426.9  738.39   436.8  740.37   544.8  753.35   554.6  757.58   564.4  770.18
   574.2   790.7   584.1  809.07   593.9  822.01   603.7  832.51   623.4  849.12
   662.6  879.88   731.4  931.07     751  944.62   760.8  950.26   780.5  960.59
#Mann= 3 , 0 , 0
       0     .06       0   397.1    .045       0   412.1      .1       0
Bank Sta=397.1,412.1
XS Rating Curve= 0 ,0
Exp/Cntr=0.3,0.1

Type RM Length L Ch R = 1 ,9191.6  ,283.8,277.5,271.2
XS GIS Cut Line= 3
     1878269.931      408155.749     1878637.279      407955.592
     1879002.707      407719.738
#Sta/Elev= 30
       0  796.78    19.9  781.83    39.8  768.28    49.8  763.24    59.8  759.29
    69.7  756.23    79.7  754.08   129.5     747   189.2  739.82     239  735.15
   268.9   732.9   288.8  732.43   348.6  732.68   398.4     735   408.4  733.72
   428.2  727.42     436  725.96     448  725.44     451  725.68   487.5  729.76
   507.3  732.66   527.1  736.89     537  740.04   546.8  745.58   576.5  767.24
   596.3  780.71   695.1   833.7   823.6  912.62   843.4  923.96   853.3   928.8
#Mann= 3 , 0 , 0
       0     .06       0     436    .045       0     451      .1       0
Bank Sta=436,451
XS Rating Curve= 0 ,0
Exp/Cntr=0.3,0.1

Type RM Length L Ch R = 1 ,8914.1  ,391,393.3,395.6
XS GIS Cut Line= 3
     1878293.479       408431.26     1878780.921      408212.264
     1879077.625      407873.174
#Sta/Elev= 30
       0  872.75    19.8  868.04    29.7  864.44    39.6  859.33    49.5  853.02
      99  818.73   118.8  804.55     188  753.25   197.9  746.72   207.8  742.69
   217.7  740.96     287  734.99   494.8  732.12   534.4  730.18   591.2  724.74
   604.5  724.39   606.2  724.51   664.5   729.2   684.6   732.2   694.6  734.38
   704.6  737.56   714.6  743.08   724.6  752.05   744.6  773.88   754.7  782.68
   784.7  807.06   894.8  887.63   924.9  908.42   954.9  929.85     985  948.34
#Mann= 3 , 0 , 0
       0      .1       0   591.2    .045       0   606.2      .1       0
Bank Sta=591.2,606.2
XS Rating Curve= 0 ,0
Exp/Cntr=0.3,0.1

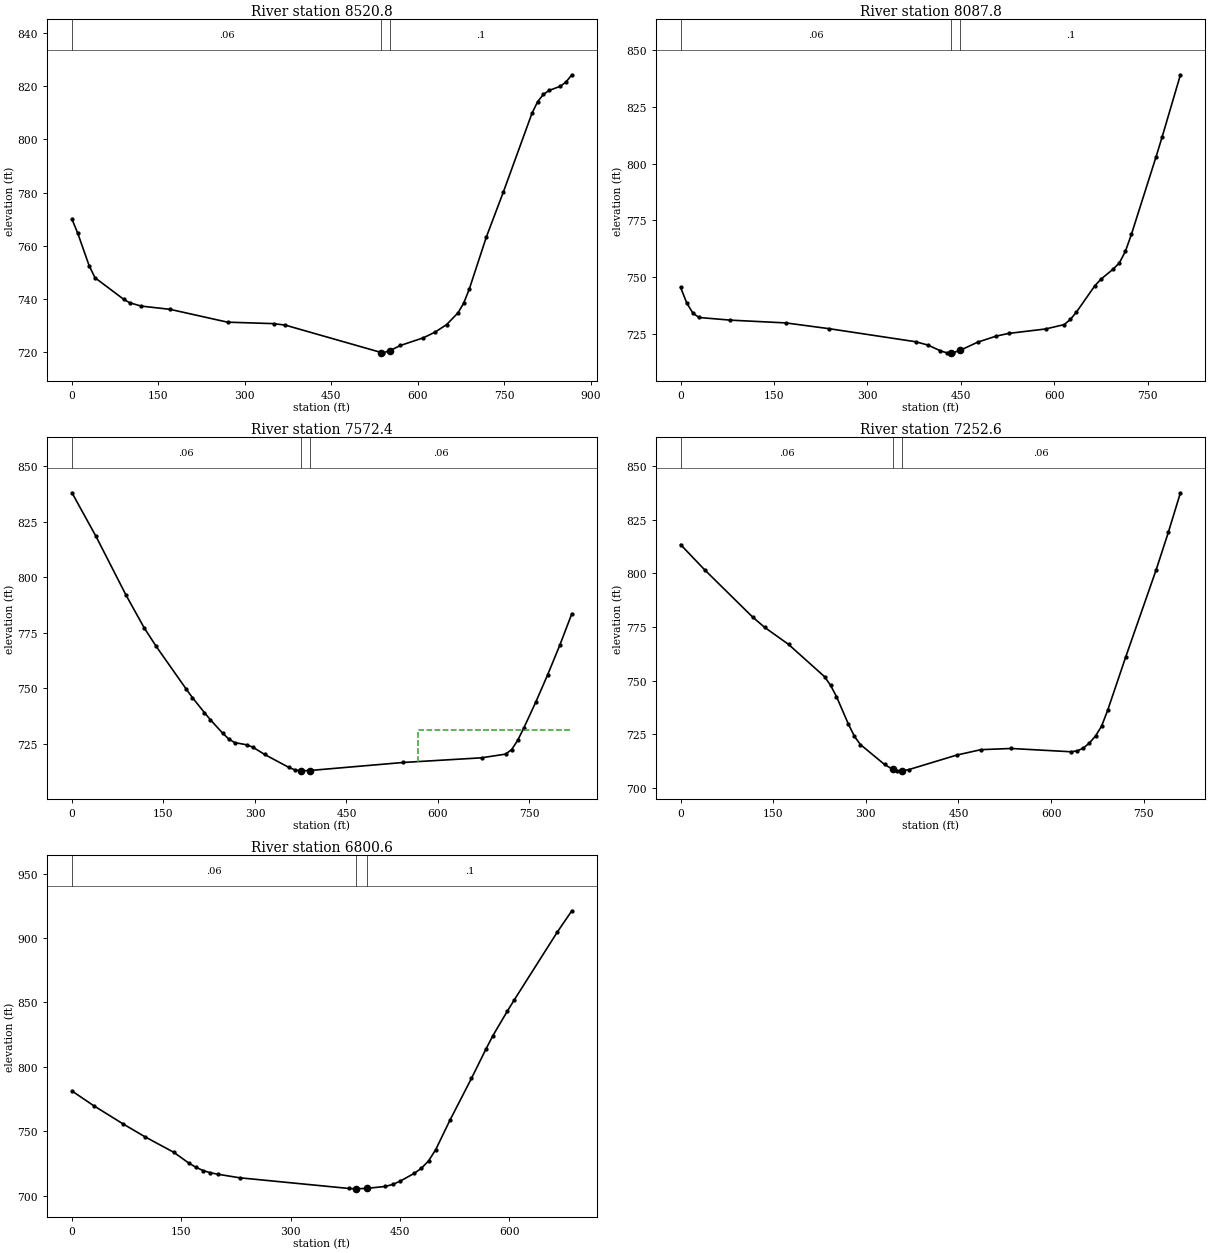
Type RM Length L Ch R = 1 ,8520.8  ,423.6,433,442.4
XS GIS Cut Line= 3
     1878712.632      408800.962       1879188.3      408358.261
     1879327.232      408191.071
#Sta/Elev= 30
       0  770.03      10  764.74      30  752.41      40  747.99      90  739.86
     100  738.61     120  737.35     170  736.13   269.9   731.3   349.9  730.75
   369.9   730.2   536.9  719.87   539.8  719.77   551.9  720.63   569.8  722.54
   609.8  725.44   629.8  727.54   649.8  730.36   669.6  734.78   679.4  738.37
   689.3  743.76     719  763.39   748.6  780.36     798  809.82   807.9  814.21
   817.8  816.94   827.7  818.42   847.4  820.02   857.3  821.67   867.2  824.32
#Mann= 3 , 0 , 0
       0     .06       0   536.9    .045       0   551.9      .1       0
Bank Sta=536.9,551.9
XS Rating Curve= 0 ,0
Exp/Cntr=0.3,0.1

Type RM Length L Ch R = 1 ,8087.8  ,522.2,515.4,508.6
XS GIS Cut Line= 3
     1878905.314      408948.052     1879487.358      408746.802
      1879635.71      408633.772
#Sta/Elev= 30
       0  745.54     9.9  738.64    19.9  734.11    29.8  732.22    79.5  731.06
   168.9  729.83   238.4  727.29   377.5  721.52   397.3  720.04   417.2  717.51
   427.1  716.66   434.1  716.64   437.1  716.63   449.1  717.77   476.8  721.32
   506.6     724   526.5  725.19   586.1  727.16   615.9  729.09   625.7  731.34
   635.5  734.62   664.9  746.17   674.8  749.11   694.4  753.54   704.2  756.23
     714  761.33   723.8  768.95   763.1  802.92   772.9  811.71   802.4  839.27
#Mann= 3 , 0 , 0
       0     .06       0   434.1    .045       0   449.1      .1       0
Bank Sta=434.1,449.1
XS Rating Curve= 0 ,0
Exp/Cntr=0.3,0.1

Type RM Length L Ch R = 1 ,7572.4  ,328.5,319.7,310.8
XS GIS Cut Line= 3
     1879207.138       409556.85     1879371.973      409373.176
     1879833.512      409034.086
#Sta/Elev= 30
       0  837.96    39.5   818.3    88.8  791.83   118.5  777.16   138.2  768.84
   187.6  749.56   197.4  745.87   217.2  739.09     227  735.86   246.8  729.93
   256.7  727.33   266.5  725.64   286.3  724.63   296.2   723.6   315.9  720.29
   355.4  714.48   365.3  713.37   374.9  712.93   375.2  712.92   389.9  713.07
     543  716.68   671.4  718.78   710.9  720.44   720.8  722.48   730.6  726.57
   740.5  732.05   760.3  743.78     780  756.22   799.8  769.45   819.5  783.58
#Mann= 3 , 0 , 0
       0     .06       0   374.9    .045       0   389.9     .06       0
#XS Ineff= 2 , 0
                          566.82          731.25
Permanent Ineff=
       F       F
Bank Sta=374.9,389.9
XS Rating Curve= 0 ,0
Exp/Cntr=0.3,0.1

Type RM Length L Ch R = 1 ,7252.6  ,443.6,452,460.3
XS GIS Cut Line= 4
      1879522.68      409787.619     1879680.451      409542.721
     1879871.494      409225.008     1880000.703      409154.181
#Sta/Elev= 30
       0  813.45    38.8  801.74   116.5  779.73     136  774.91   174.8  766.94
   233.1  751.91   242.8  747.92   252.5  742.61   271.9   729.7   281.6  724.06
   291.3  720.25   330.3  710.98   343.6   708.7   349.9  708.06   358.6  708.02
   369.4  708.58   447.4  715.38   486.4  717.89   535.2  718.44   632.8   716.9
   642.5  717.35   652.3  718.62     662     721   671.9  724.24   681.7  728.83
   691.5  736.16     721  761.23   770.1  801.67   789.8  819.11   809.4  837.57
#Mann= 3 , 0 , 0
       0     .06       0   343.6    .045       0   358.6     .06       0
Bank Sta=343.6,358.6
XS Rating Curve= 0 ,0
Exp/Cntr=0.3,0.1

Type RM Length L Ch R = 1 ,6800.6  ,419.1,414.7,410.3
XS GIS Cut Line= 3
     1879798.191      409907.714     1880153.764      409632.203
     1880344.502       409493.27
#Sta/Elev= 30
       0  781.19      30   769.7      70  755.67     100  745.68   139.9  733.51
   159.9  725.37   169.9  722.01   179.9  719.41   189.9  717.72   199.9  716.58
   229.9  713.81   379.8  705.52   389.8  705.22   390.1  705.22   405.1  705.62
   429.8  707.08   439.8   708.6   449.8  711.04   469.5  717.22   479.3  721.16
   489.2  726.88     499  735.63   518.6  758.55   548.1     791   567.8  813.52
   577.6  824.25   597.3  843.18   607.1  852.18   666.1  904.78   685.8   921.1
#Mann= 3 , 0 , 0
       0     .06       0   390.1    .045       0   405.1      .1       0
Bank Sta=390.1,405.1
XS Rating Curve= 0 ,0
Exp/Cntr=0.3,0.1