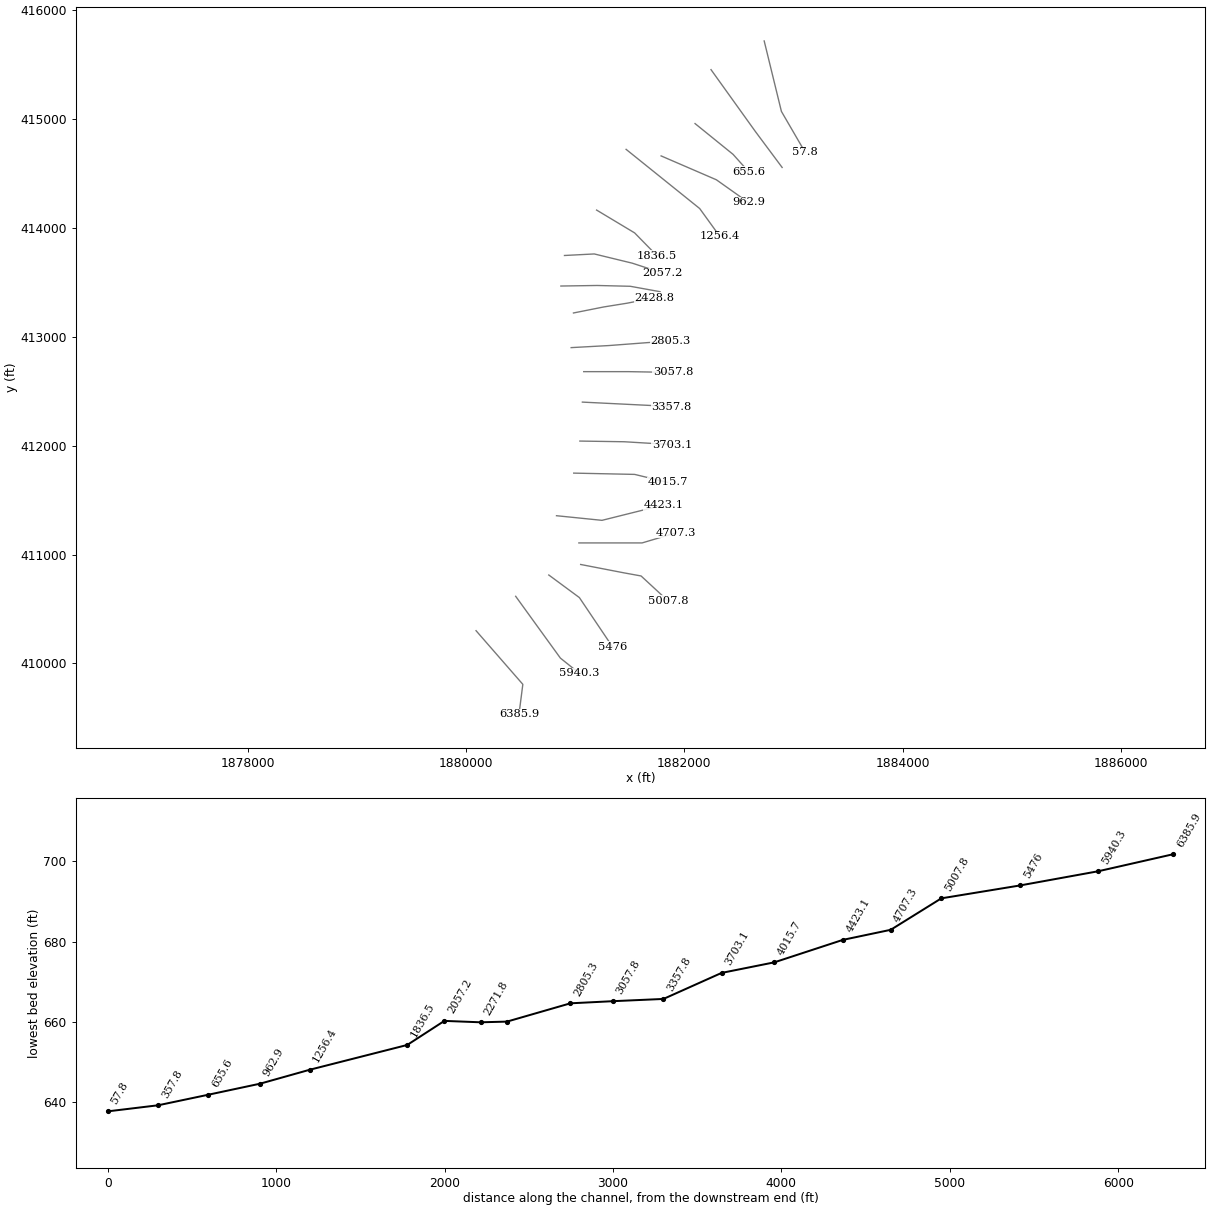
HEC-RAS study ArmstrngCk.prj: ArmstrngCk

--- ArmstrngCk.g01 (geometry) --- (continued)

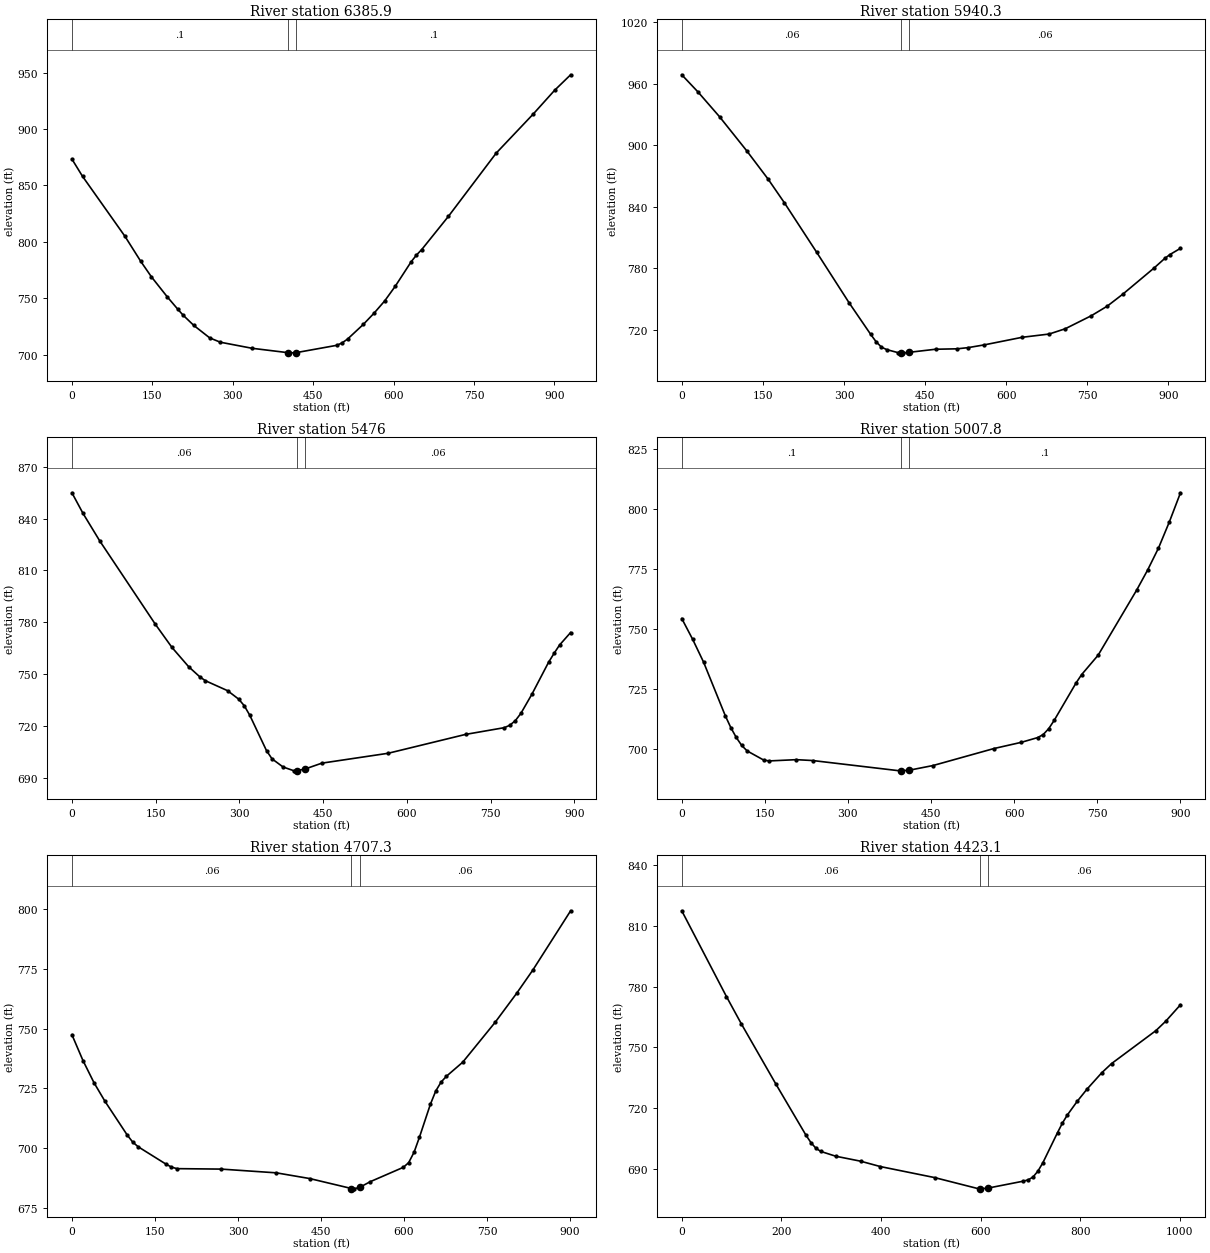
Type RM Length L Ch R = 1 ,6385.9  ,447.7,445.6,443.6
XS GIS Cut Line= 3
      1880092.54      410300.964     1880521.117      409808.817
      1880485.79      409533.302
#Sta/Elev= 30
       0  873.38    19.8   858.1    98.9  805.02   128.5  782.77   148.3  769.12
     178  751.31   197.8  740.26   207.6  735.07   227.4  726.08   257.1  715.02
   276.9  711.21   336.2  705.83   403.5  701.92   415.3   701.8   418.5  701.99
   494.4  708.49   504.3  710.69   514.2  713.97   543.8  727.06   563.6  736.89
   583.4  747.72   603.2  760.76   632.8  782.39   642.7  788.36   652.6  793.27
   702.2  822.55   791.5  878.66   860.9  913.41   900.6  934.35   930.4  948.04
#Mann= 3 , 0 , 0
       0      .1       0   403.5    .045       0   418.5      .1       0
Bank Sta=403.5,418.5
XS Rating Curve= 0 ,0
Exp/Cntr=0.3,0.1

Type RM Length L Ch R = 1 ,5940.3  ,465.1,464.3,463.5
XS GIS Cut Line= 4
     1880455.673      410616.346     1880695.244      410284.538
     1880865.319      410049.296     1881039.166      409910.068
#Sta/Elev= 30
       0  968.57      30  951.85    69.9  927.66   119.8  894.71   159.7  866.87
   189.7  843.89   249.6  795.48   309.4  746.39   349.4  715.54   359.4  708.38
   369.3  703.08   379.3  700.66   399.3  697.84   405.9  697.65   409.3  697.55
   420.9  698.08   469.3  701.05   509.4  701.48   529.4  702.62   559.4   705.3
   629.5   712.7   679.5  715.88   709.2  721.02   757.6  733.78   786.7     743
   815.7  754.75   873.8  780.39   893.2  789.55   902.9  793.39   922.3  799.42
#Mann= 3 , 0 , 0
       0     .06       0   405.9    .045       0   420.9     .06       0
Bank Sta=405.9,420.9
XS Rating Curve= 0 ,0
Exp/Cntr=0.3,0.1

Type RM Length L Ch R = 1 ,5476    ,449,468.2,487.5
XS GIS Cut Line= 3
     1880758.945      410811.953     1881039.166      410604.732
     1881342.934      410152.612
#Sta/Elev= 30
       0  854.97    19.9  843.02    49.8  827.13   149.4  778.87   179.2  765.44
   209.1  754.28     229  748.44     239  746.19   278.8  740.41   298.7  735.51
   308.7  731.69   318.6  726.15   348.5  705.71   358.4  700.95   378.2  696.23
     398  694.01   402.8  694.09   417.8   695.1   447.6  698.46   566.4  704.18
     705   715.1   774.4     719   784.3   720.4   794.2  723.09   804.1  727.27
   823.9   738.4   853.6   756.8   863.5  762.01   873.4  766.86   893.2  774.09
#Mann= 3 , 0 , 0
       0     .06       0   402.8    .045       0   417.8     .06       0
Bank Sta=402.8,417.8
XS Rating Curve= 0 ,0
Exp/Cntr=0.3,0.1

Type RM Length L Ch R = 1 ,5007.8  ,297.6,300.4,303.3
XS GIS Cut Line= 4
     1881050.939        410908.5     1881447.194       410831.75
     1881604.417      410803.094     1881851.568       410574.12
#Sta/Elev= 30
       0  754.33    19.7  745.64    39.4  736.13    78.8  713.67    88.6  708.81
    98.4  704.71   108.3  701.36   118.1  699.09   147.7  695.31   157.5  694.92
   206.7  695.45   236.3  695.09   393.8  690.79   396.1  690.81   411.1  691.07
   453.6     693   563.4  700.08     613  702.68   642.7  704.67   652.6  705.94
   662.5  708.38   672.4  711.85   712.1  727.53     722  730.95   751.7  739.02
   821.1   766.1   840.9  774.46   860.7  783.71   880.5  794.73   900.4  806.77
#Mann= 3 , 0 , 0
       0      .1       0   396.1    .045       0   411.1      .1       0
#XS Ineff= 2 , 0
          206.69  695.44
Permanent Ineff=
       F       F
Bank Sta=396.1,411.1
XS Rating Curve= 0 ,0
Exp/Cntr=0.3,0.1

Type RM Length L Ch R = 1 ,4707.3  ,278.7,284.2,289.6
XS GIS Cut Line= 3
     1881034.456      411106.302     1881613.735      411106.302
     1881922.212      411198.139
#Sta/Elev= 30
       0  747.44      20  736.62      40  727.31    59.9  719.51    99.9  705.47
   109.9   702.5   119.8  700.54   169.8  693.31   179.8  692.05   189.8   691.4
   269.7  691.21   369.5  689.64   429.5  687.26   505.1  683.09   509.4  682.95
   520.1   683.6   539.3  685.97   598.8  691.95   608.5  693.92   618.3  698.32
     628  704.61   647.6  718.27   657.3  723.85   667.1  727.64   676.8  730.08
   706.1  735.93   764.6  752.59   803.6  764.77   832.9  774.53   901.1  799.29
#Mann= 3 , 0 , 0
       0     .06       0   505.1    .045       0   520.1     .06       0
Bank Sta=505.1,520.1
XS Rating Curve= 0 ,0
Exp/Cntr=0.3,0.1

Type RM Length L Ch R = 1 ,4423.1  ,413.1,407.1,401
XS GIS Cut Line= 3
     1880829.589       411355.91     1881246.387      411313.524
     1881811.537      411454.811
#Sta/Elev= 30
       0  817.28    89.8  775.04   119.7  761.61   189.5  731.79   249.4  706.86
   259.4   703.2   269.3  700.44   279.3  698.84   309.2  696.49   359.1  694.05
     399  691.39   507.8  685.98   596.7  680.44   599.2  680.45   614.2  680.77
   685.5   684.2   695.4  684.82   705.3  686.24   715.2  689.15     725   693.2
   754.6  708.11   764.5  712.84   774.4  716.81   794.1   723.5   813.9  729.53
   843.5  737.59   863.3  742.12   952.1  758.29   971.9  762.93  1001.5  771.03
#Mann= 3 , 0 , 0
       0     .06       0   599.2    .045       0   614.2     .06       0
Bank Sta=599.2,614.2
XS Rating Curve= 0 ,0
Exp/Cntr=0.3,0.1

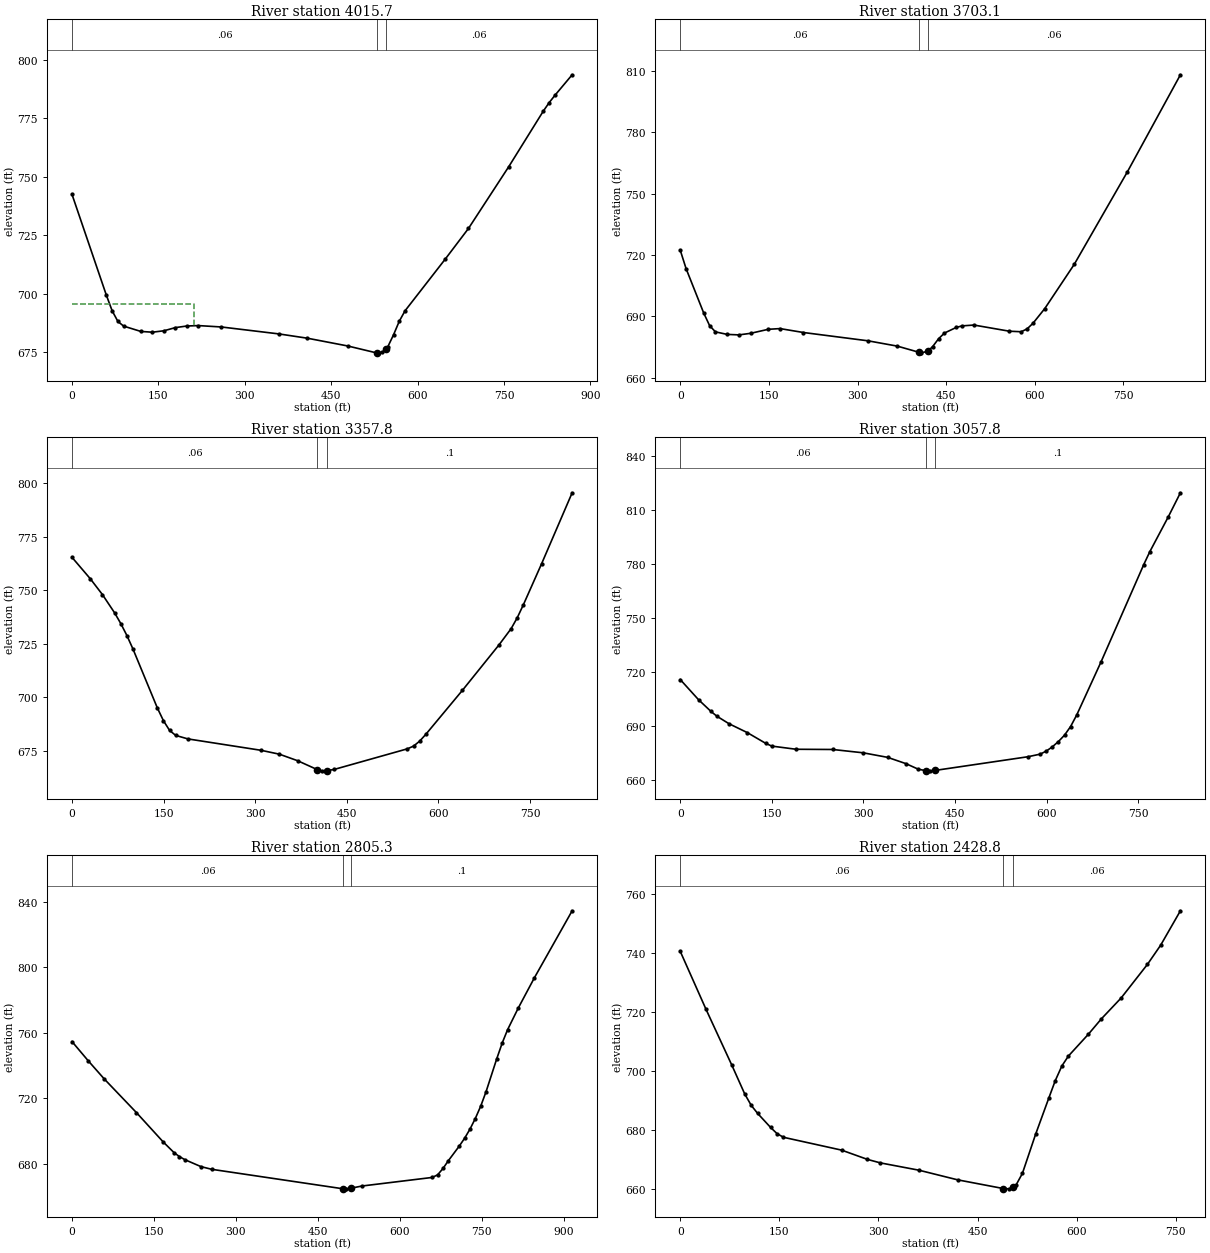
Type RM Length L Ch R = 1 ,4015.7  ,313,312.8,311.7
XS GIS Cut Line= 3
      1880987.36      411746.806     1881545.446      411735.032
     1881846.859      411662.033
#Sta/Elev= 30
       0  742.47    59.8  699.35    69.8  692.75    79.7  688.23    89.7  686.24
   119.6  683.97   139.6  683.65   159.5  684.25   179.4   685.6   199.4  686.29
   219.3  686.47   259.2  685.88   358.8  682.93   408.7  681.08   478.5  677.78
   528.3  674.84     530  674.87   538.3  675.01     545  676.63   548.2   677.4
   558.2  682.52   568.2  688.34   578.2  692.79   648.2  714.91   688.3  727.92
   758.3  754.31   818.3  778.03   828.3  781.58   838.3  784.71   868.3   793.5
#Mann= 3 , 0 , 0
       0     .06       0     530    .045       0     545     .06       0
#XS Ineff= 2 , 0
          212.58  695.66
Permanent Ineff=
       F       F
Bank Sta=530,545
XS Rating Curve= 0 ,0
Exp/Cntr=0.3,0.1

Type RM Length L Ch R = 1 ,3703.1  ,345.7,345.3,345.8
XS GIS Cut Line= 3
     1881043.558      412040.879     1881450.803      412034.571
     1881889.245      412008.187
#Sta/Elev= 30
       0  722.43     9.9  713.39    39.7   691.7    49.7  685.52    59.6  682.46
    79.5  681.23    99.3  680.99   119.2  681.76     149  683.72   168.9  684.07
   208.6  682.15   317.9  678.09   367.6  675.48   403.7  672.51   407.3  672.21
   418.7  672.93   427.3   675.3   437.2   679.1   447.2  681.89   467.2  684.65
   477.2   685.4   497.1   685.8     557  682.79     577  682.53     587  683.91
     597  686.67   616.9  693.84   666.8  715.47   756.7  760.71   846.5  808.21
#Mann= 3 , 0 , 0
       0     .06       0   403.7    .045       0   418.7     .06       0
Bank Sta=403.7,418.7
XS Rating Curve= 0 ,0
Exp/Cntr=0.3,0.1

Type RM Length L Ch R = 1 ,3357.8  ,298.9,300,300.7
XS GIS Cut Line= 3
     1881066.549      412398.383     1881475.551      412378.185
     1881884.553      412357.987
#Sta/Elev= 30
       0  765.44      30  755.42    49.9  748.02    69.9  739.46    79.9  734.51
    89.9  728.92    99.9  722.59   139.8  695.07   149.8  689.11   159.8   684.6
   169.8  682.27   189.8  680.63   309.6  675.31   339.6   673.5   369.6  670.43
     402  666.25   409.5  665.72     417  665.77   429.5  666.39   549.3  676.01
   559.3  677.28   569.3  679.59   579.3  682.74   639.2  703.28   699.2  724.54
   719.1  732.14   729.1  737.22   739.1  743.27   769.1  762.52     819  795.58
#Mann= 3 , 0 , 0
       0     .06       0     402    .045       0     417      .1       0
Bank Sta=402,417
XS Rating Curve= 0 ,0
Exp/Cntr=0.3,0.1

Type RM Length L Ch R = 1 ,3057.8  ,250.7,252.4,254.5
XS GIS Cut Line= 3
     1881078.922      412677.808     1881488.503      412677.873
     1881897.923      412670.561
#Sta/Elev= 30
       0  715.87      30  704.65      50  698.26    59.9  695.52    79.9  691.32
   109.9  686.38   139.9  680.44   149.8  678.91   189.8  677.14   249.7  677.02
   299.7  675.17   339.6  672.65   369.6  669.16   389.6   666.1   402.1  665.25
   409.6  665.16   417.1  665.38   569.4  672.99   589.4  674.43   599.3   676.1
   609.3  678.47   619.3  681.42   629.3  684.97   639.3  689.78   649.3  696.18
   689.2  725.73   759.1  779.73   769.1  786.94   799.1  806.13   819.1  819.59
#Mann= 3 , 0 , 0
       0     .06       0   402.1    .045       0   417.1      .1       0
Bank Sta=402.1,417.1
XS Rating Curve= 0 ,0
Exp/Cntr=0.3,0.1

Type RM Length L Ch R = 1 ,2805.3  ,374.7,376.6,379.2
XS GIS Cut Line= 3
     1880963.812      412898.298     1881307.612      412917.137
     1881877.261      412960.374
#Sta/Elev= 30
       0  754.53    29.5  742.88      59  731.73     118  711.16   167.2  693.18
   186.9  686.71   196.8  684.29   206.6  682.44   236.1  678.19   255.8  676.55
   496.4  664.65   501.9  664.63   511.4  665.08   531.5  666.38   659.5  671.59
   669.4   673.2   679.2  677.08   689.1  681.87   708.8  690.66   718.6  695.44
   728.5  701.04   738.3  707.55   748.2  715.09     758  723.94   777.7  744.17
   787.6  753.68   797.4  761.77   817.1  775.09   846.6  793.54   915.6  834.36
#Mann= 3 , 0 , 0
       0     .06       0   496.4    .045       0   511.4      .1       0
Bank Sta=496.4,511.4
XS Rating Curve= 0 ,0
Exp/Cntr=0.3,0.1

Type RM Length L Ch R = 1 ,2428.8  ,161,156.9,151.1
XS GIS Cut Line= 4
     1880985.005      413216.195     1881262.898      413271.547
     1881474.802      413305.677     1881729.119      413355.128
#Sta/Elev= 30
       0  740.52    39.1  720.84    78.2  701.91    97.7  692.17   107.5  688.33
   117.2  685.61   136.8  680.86   146.6  678.76   156.3  677.53   244.3  673.18
   283.4  670.04   302.9  668.86   361.4  666.38   419.9  663.12   489.3  660.16
     498  660.07   504.3  660.81     508  661.24   517.9  665.29   537.8  678.48
   557.8  690.76   567.7  696.73   577.7  701.71   587.7  705.09   617.6  712.39
   637.5  717.66   667.4  724.73   707.2  736.11   727.2   742.6   757.1  754.26
#Mann= 3 , 0 , 0
       0     .06       0   489.3    .045       0   504.3     .06       0
Bank Sta=489.3,504.3
XS Rating Curve= 0 ,0
Exp/Cntr=0.3,0.1

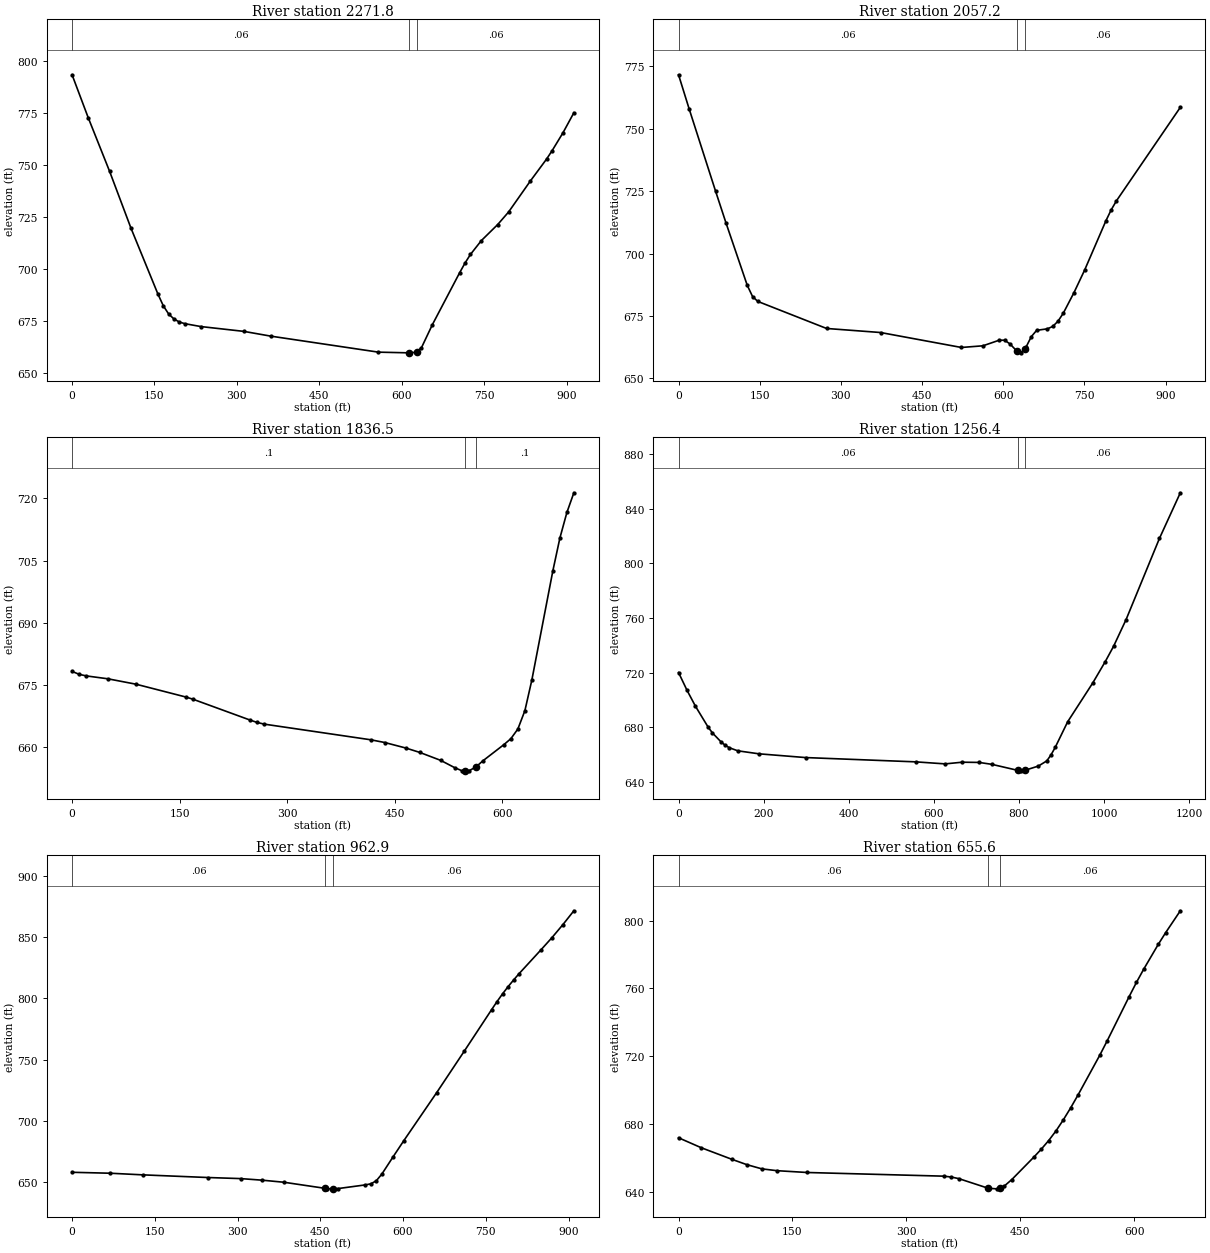
Type RM Length L Ch R = 1 ,2271.8  ,219.5,214.7,209
XS GIS Cut Line= 4
     1880869.621      413463.448      1881201.68      413468.502
     1881505.414      413461.093     1881778.246      413411.537
#Sta/Elev= 30
       0  793.21    29.3   772.7    68.4  746.85   107.4  719.54   156.3  688.05
     166  682.48   175.8  678.51   185.6   676.1   195.4  674.67   205.1  673.89
   234.4   672.5   312.6  670.19   361.5  667.91   557.5  660.23   612.6   659.9
   626.1  660.16   627.6   660.5   635.9  662.39   655.7   673.4   705.2  698.24
   715.2  702.99     725  707.08   744.9  713.73   774.6  721.41   794.4  727.42
     834  742.27   863.7  752.86   873.6  756.81   893.4   765.4   913.2     775
#Mann= 3 , 0 , 0
       0     .06       0   612.6    .045       0   627.6     .06       0
Bank Sta=612.6,627.6
XS Rating Curve= 0 ,0
Exp/Cntr=0.3,0.1

Type RM Length L Ch R = 1 ,2057.2  ,233.3,220.7,209.9
XS GIS Cut Line= 4
     1880902.588      413743.668     1881175.743      413757.797
     1881524.252      413673.025     1881804.473      413581.188
#Sta/Elev= 30
       0  771.61    19.5  758.02    68.4  725.02    87.9  712.14     127  687.26
   136.8  682.78   146.5  680.84   273.5  670.01   373.2  668.39   522.6   662.4
   562.4  663.07   592.3   665.3   602.3  665.31   612.3  663.84   624.6  661.06
   632.2  660.25   639.6  661.97     642  662.53   651.8  666.75   661.7  669.27
   681.3  669.86   691.2   670.8     701  672.89   710.8   676.1   730.5  684.31
   750.2  693.35   789.5  713.08   799.3  717.49   809.1  721.14   927.1  758.57
#Mann= 3 , 0 , 0
       0     .06       0   624.6    .045       0   639.6     .06       0
Bank Sta=624.6,639.6
XS Rating Curve= 0 ,0
Exp/Cntr=0.3,0.1

Type RM Length L Ch R = 1 ,1836.5  ,577.3,580,582.6
XS GIS Cut Line= 3
     1881196.937      414160.466     1881545.446       413950.89
     1881750.312      413741.314
#Sta/Elev= 30
       0  678.26     9.9  677.55    19.8  677.17    49.6  676.48    89.3  675.16
   158.7  672.07   168.6  671.54     248  666.52   257.9  665.94   267.8  665.53
   416.4  661.75     436  661.09   465.3  659.76   484.8   658.7   514.1  656.77
   533.7     655   543.4  654.29   547.9  654.27   553.2  654.25   562.9  655.15
   572.8  656.66     602  660.56   611.8     662   621.6  664.34   631.4  668.77
   641.1  676.16   670.4  702.53   680.2  710.44     690  716.64   699.7  721.38
#Mann= 3 , 0 , 0
       0      .1       0   547.9    .045       0   562.9      .1       0
Bank Sta=547.9,562.9
XS Rating Curve= 0 ,0
Exp/Cntr=0.3,0.1

Type RM Length L Ch R = 1 ,1256.4  ,287.4,293.5,299.6
XS GIS Cut Line= 3
     1881467.337      414717.442     1882141.208      414174.595
     1882324.881      413920.278
#Sta/Elev= 30
       0  720.05    19.9  707.05    39.8  695.34    69.6  680.03    79.6  675.83
    99.5  669.38   109.4  666.82   119.4  664.97   139.2  662.72     189  660.52
   298.4  657.78     557  654.64   626.6  653.15   666.4  654.38   706.2  654.22
     736  652.83     798  648.34   805.6  648.06     813  648.37   845.4  651.55
   865.3  655.35   875.1  659.72   884.9  665.15   914.3  683.99   973.2  712.38
  1002.6  728.02  1022.2  739.26  1051.6  758.84    1130  818.28    1179  851.64
#Mann= 3 , 0 , 0
       0     .06       0     798    .045       0     813     .06       0
Bank Sta=798,813
XS Rating Curve= 0 ,0
Exp/Cntr=0.3,0.1

Type RM Length L Ch R = 1 ,962.9   ,313.3,307.3,301.2
XS GIS Cut Line= 3
     1881787.989      414657.327     1882294.269      414438.332
     1882586.263       414231.11
#Sta/Elev= 30
       0   658.1      69  657.34     128  656.01   246.3  653.83   305.4  652.96
   344.8  651.66   384.2  649.97   458.8     645     463  644.74   472.8   644.6
   473.8  644.63   482.7  644.85   531.9  647.83   541.8  648.71   551.6  651.21
   561.6  656.64   581.4  670.32   601.3  683.82     661  723.09   710.8  756.76
   760.5  790.72   770.4  797.35   780.4  803.65   790.3  809.44   800.3  814.89
   810.2  820.04     850  839.53   869.9  849.47   889.8  860.13   909.7  871.43
#Mann= 3 , 0 , 0
       0     .06       0   458.8    .045       0   473.8     .06       0
Bank Sta=458.8,473.8
XS Rating Curve= 0 ,0
Exp/Cntr=0.3,0.1

Type RM Length L Ch R = 1 ,655.6   ,304,297.8,292.1
XS GIS Cut Line= 3
     1882098.822      414954.031     1882447.331      414671.456
     1882588.618      414513.685
#Sta/Elev= 30
       0  671.95    29.9  666.08    69.8  659.32    89.7  656.13   109.7  653.62
   129.6  652.55   169.5  651.48     349  649.32   358.9  648.82   368.9  647.87
   407.7  642.19   418.8  641.85   422.7  642.48   428.7  643.46   438.7  647.33
   467.9  660.64   477.6  665.29   487.2  670.31   496.8  675.97   506.4  682.45
   516.1  689.54   525.7  697.05   554.6   720.7   564.2  729.07   593.1  755.12
   602.7  763.49   612.3  771.31   631.6  786.04   641.2  792.85   660.5  805.73
#Mann= 3 , 0 , 0
       0     .06       0   407.7    .045       0   422.7     .06       0
Bank Sta=407.7,422.7
XS Rating Curve= 0 ,0
Exp/Cntr=0.3,0.1

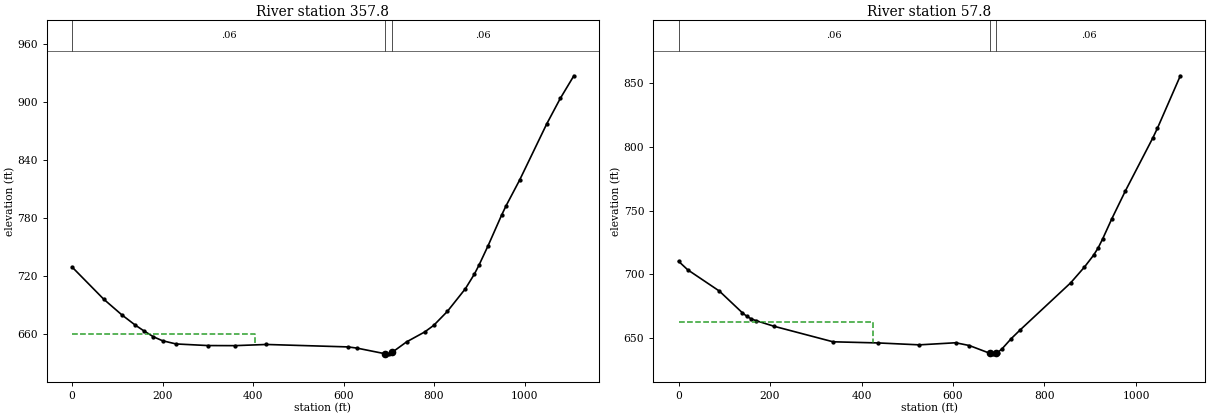
Type RM Length L Ch R = 1 ,357.8   ,302.6,300,297.4
XS GIS Cut Line= 3
     1882245.115      415448.924     1882652.332      414880.104
     1882896.682      414551.496
#Sta/Elev= 30
       0     729      70  695.72   109.9  679.57   139.9  668.85   159.9  662.64
   179.9  656.85   199.9  652.76   229.8  649.45   299.8  647.79   359.8  647.69
   429.7  648.91   609.6  646.39   629.6  645.16   692.1  639.28   699.6  639.22
   707.1  640.64   739.5  651.63   779.5  661.87   799.4  668.69   829.4  683.05
   869.4   706.6   889.3  721.74   899.3  730.83   919.3   750.8   949.2  782.47
   959.2  792.26   989.2   818.9  1049.1  876.97  1079.1  903.36  1109.1  926.77
#Mann= 3 , 0 , 0
       0     .06       0   692.1    .045       0   707.1     .06       0
#XS Ineff= 2 , 0
           403.9  660.05
Permanent Ineff=
       F       F
Bank Sta=692.1,707.1
XS Rating Curve= 0 ,0
Exp/Cntr=0.3,0.1

Type RM Length L Ch R = 1 ,57.8    ,57.6,57.8,57.5
XS GIS Cut Line= 4
      1882732.26      415712.274     1882890.046      415065.713
     1882901.003      415046.693     1883106.456      414692.462
#Sta/Elev= 30
       0  710.43    19.9  703.73    89.4  686.95   139.1  670.08     149  667.24
   158.9  665.17   168.9  663.83   208.6  659.37   337.7  647.16   437.1  646.25
   526.5  644.76   605.9   646.4   635.7  644.23     680   638.2   687.5   637.7
     695  638.43   697.5  638.67   707.5  641.74   727.4  649.68   747.4  656.67
   857.3  693.47   887.2  705.76   907.2  715.08   917.2  720.78   927.2  727.95
   947.2  743.73   977.1  765.79  1037.1  807.41    1047   814.9    1097  856.04
#Mann= 3 , 0 , 0
       0     .06       0     680    .045       0     695     .06       0
#XS Ineff= 2 , 0
          425.15  662.33
Permanent Ineff=
       F       F
Bank Sta=680,695
XS Rating Curve= 0 ,0
Exp/Cntr=0.3,0.1

Chan Stop Cuts=-1
Use User Specified Reach Order=0
Composite Channel Slope=5